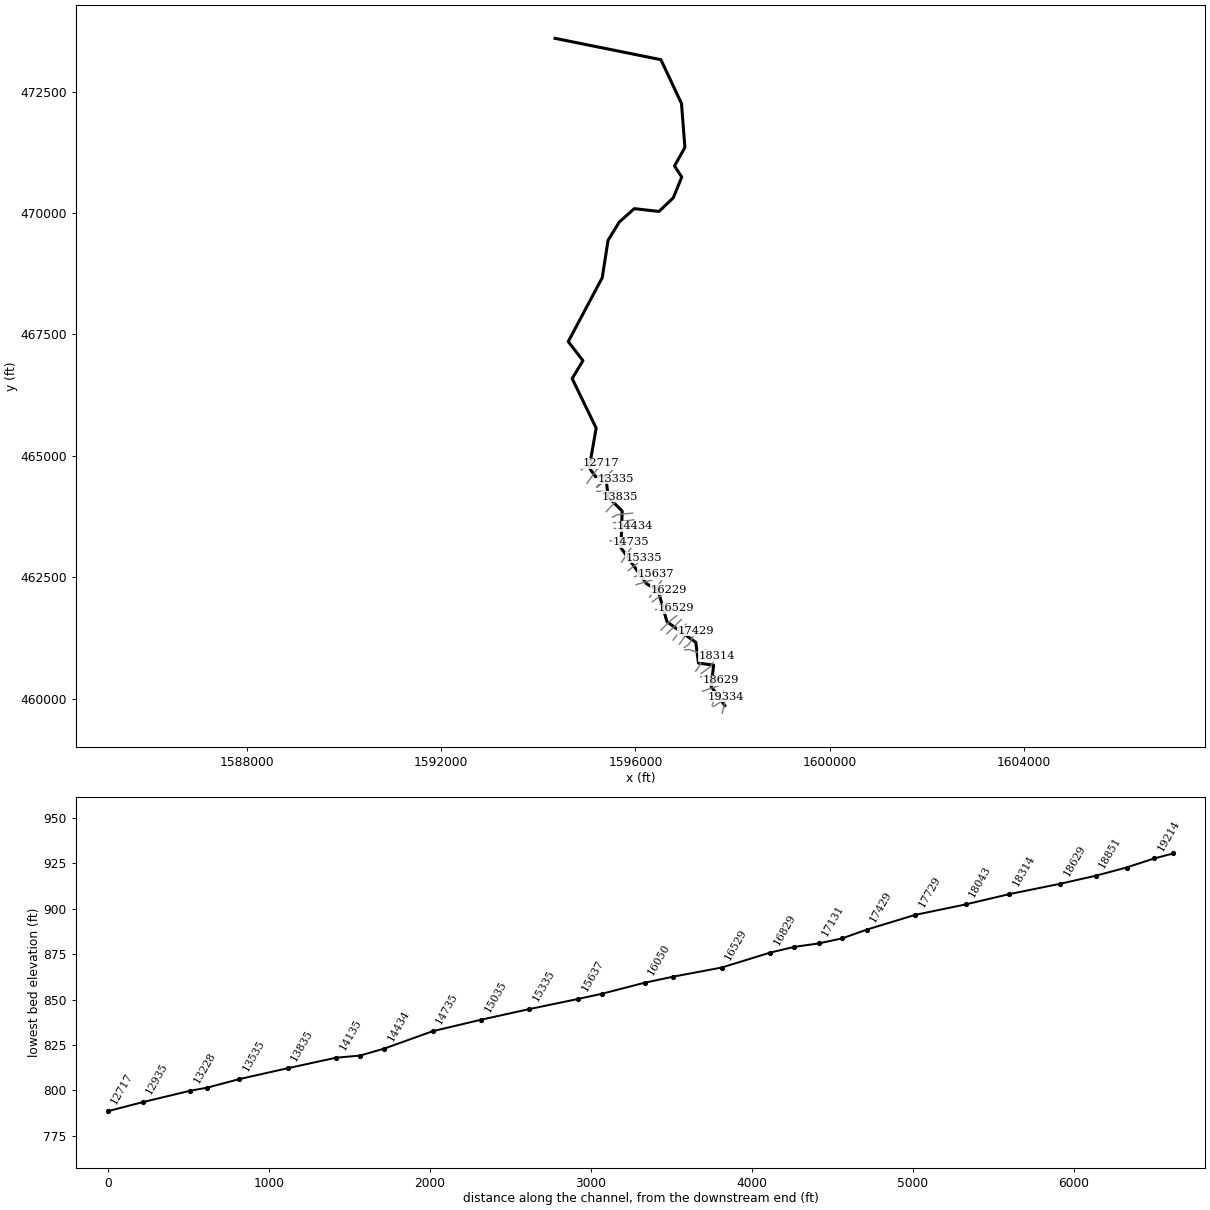
--- CoonRn.prj (project) ---

Proj Title=CoonRn
Current Plan=p01
Default Exp/Contr=0,0
English Units
Geom File=g01
Flow File=f01
Plan File=p01
BEGIN DESCRIPTION:
---------- MODELED AS PART OF WVEM CTP PROGRAM, 2025----------
Stream Name: Coon Run
Flood Zone: AFH
Marshall County, WV
HEC-RAS Version: RAS 6.6
Vertical Datum: NAVD88
Projection: NAD 1983 StatePlane West Virginia N FIPS 4701 (US Feet)
Terrain: 1-meter West Virginia FEMA R3 South Central (collected 2018-2019)
Land Use: 2024 NLCD
Hydrologic Method:
Duda et al., "Estimation of magnitude and frequency of floods for rural, unregulated streams in and near Virginia and West Virginia." September 8, 2025.
Additional Model Notes:
None
END DESCRIPTION:
DSS Export Rating Curves= 0
DSS Export Rating Curve Sorted= 0
DSS Export Volume Flow Curves= 0
DXF OffsetX= 0
DXF OffsetY= 0
DXF ScaleX= 0
DXF ScaleY= 0

--- CoonRn.p01 (plan) ---

Plan Title=Floodplain
Program Version=6.60
Short Identifier=Floodplain
Geom File=g01
Flow File=f01
Subcritical Flow
K Sum by GR= 0
Std Step Tol= 0.01
Critical Tol= 0.01
Num of Std Step Trials= 20
Max Error Tol= 0.3
Flow Tol Ratio= 0.001
Split Flow NTrial= 30
Split Flow Tol= 0.02
Split Flow Ratio= 0.02
Log Output Level= 0
Friction Slope Method= 1
Unsteady Friction Slope Method= 2
Unsteady Bridges Friction Slope Method= 1
Parabolic Critical Depth
Global Vel Dist= 0 , 0 , 0
Global Log Level= 0
CheckData=False
Encroach Param=-1 ,0,0, 0
Flow Ratio Tolerance=0.1
Flow Ratio Min Ratio=0.5
Flow Ratio Max Ratio=4
Flow Ratio Max Iterations= 10
Mapping Interval=1HOUR
Computation Time Step Use Courant=        0
Computation Time Step Use Time Series=    0
Computation Time Step Count To Double=0
Computation Time Step Max Doubling=0
Computation Time Step Max Halving=0
Computation Time Step Residence Courant=0
Run HTab= 0
Run UNet= 0
Run Sediment= 0
Run PostProcess= 0
Run WQNet= 0
Run RASMapper=-1
UNET Theta= 0
UNET Theta Warmup= 0
UNET ZTol= 0
UNET ZSATol= 0
UNET MxIter= 0
UNET Max Iter WO Improvement= 0
UNET MaxInSteps= 0
UNET DtIC= 0
UNET DtMin= 0
UNET MaxCRTS= 0
UNET WFStab= 0
UNET SFStab= 0
UNET WFX= 1
UNET SFX= 1
UNET Gravity=32.17405
UNET 1D Methodology=Finite Difference
UNET DSS MLevel= 1
UNET Pardiso=0
UNET DZMax Abort= 0
UNET Use Existing IB Tables= 0
UNET Froude Reduction=False
UNET Froude Limit= 0
UNET Froude Power= 0
UNET D1 Cores= 0
UNET WindReference=Eulerian
UNET WindDragFormulation=Hsu (1988)
UNET D2 Coriolis=0
UNET D2 Cores= 0
UNET D2 Theta= 1
UNET D2 Theta Warmup= 1
UNET D2 Z Tol= 0.01
UNET D2 Volume Tol= 0.01
UNET D2 Max Iterations= 20
UNET D2 Advanced Convergence=0
UNET D2 WS Max Tol=0.15
UNET D2 WS RMS Tol=0.002
UNET D2 WS Stall Tol=1
UNET D2 Equation= 0
UNET D2 RampUpFraction=0.1
UNET D2 TimeSlices= 1
UNET D2 Turbulence Formulation=Non-Conservative (original)
UNET D2 Eddy Viscosity=0.3
UNET D2 Transverse Eddy Viscosity=0.1
UNET D2 Smagorinsky Mixing=0
UNET D2 BCVolumeCheck=0
UNET D2 Cores=0
UNET D2 SolverType=PARDISO (Direct)
UNET D2 Minimum Iterations= 3
UNET D2 Maximum Iterations= 30
UNET D2 Restart Number= 10
UNET D2 Relaxation Coeff=1.3
UNET D2 SOR Precondition Iterations= 10
UNET D2 ILUT Maximum Fill= 8
UNET D2 ILUT Tolerance=1E-08
UNET D2 Convergence Tolerance=0.00001
PS Theta= 1
PS WS Tol= 0.01
PS Volume Tol= 0.01
PS Max Iterations= 20
PS Equation= 0
PS Advance Time Step=-1
PS Target Courant=0.9
PS Time Slices= 1
PS Iterate With 2D=0
PS Project Initial WSE from DS=-1
PS Ramp Up Initial WSE from US=-1
PS Cores=0
UNET D1D2 MaxIter= 0
UNET D1D2 ZTol=0.01
UNET D1D2 QTol=0.1
UNET D1D2 MinQTol=1
Write IC File= 0
Write IC File at Fixed DateTime=0
Write IC File at Sim End=0
Echo Input=False
Echo Parameters=False
Echo Output=False
Write Detailed= 0
HDF Write Warmup=0
HDF Write Time Slices=0
HDF Flush=0
HDF Compression= 1
HDF Chunk Size= 1
HDF Spatial Parts= 1
HDF Use Max Rows=0
HDF Fixed Rows= 1
Calibration Method= 0
Calibration Iterations= 20
Calibration Max Change=0.05
Calibration Tolerance=0.2
Calibration Maximum=1.5
Calibration Minimum=0.5
Calibration Optimization Method= 1
WQ AD Non Conservative
WQ ULTIMATE=-1
WQ Max Comp Step=1HOUR
WQ Output Interval=15MIN
WQ Output Selected Increments= 0
WQ Create Restart=0
WQ Fixed Restart=0
WQ System Summary=0
WQ Write To DSS=0
Sorting and Armoring Iterations= 10
XS Update Threshold= 0.02
Bed Roughness Predictor= 0
Processes Affected by Predictor=Sediment Only
Hydraulics Update Threshold= 0.02
Energy Slope Method= 1
Volume Change Method= 1
Sediment Retention Method= 0
Sediment TS Multiplier= 1
Warm Up Method= 0
XS Weighting Method= 0
Number of US Weighted Cross Sections= 1
Number of DS Weighted Cross Sections= 1
Upstream XS Weight=0
Main XS Weight=1
Downstream XS Weight=0
Number of DS XS's Weighted with US Boundary= 1
Upstream Boundary Weight= 1
Weight of XSs Associated with US Boundary= 0
Number of US XS's Weighted with DS Boundary= 1
Downstream Boundary Weight= 0.5
Weight of XSs Associated with DS Boundary= 0.5
Percentile Method= 0
Sediment Output Level= 3
Mass or Volume Output= 0
Output Increment Type= 1
Profile and TS Output Increment= 1
Transport Output Increment 1
XS Output Flag= 0
XS Output Increment= 10
Read HDF5 Sediment Hotstart= 0
Sediment Hotstart Type= 0
Write Gradation File= 0
Read Gradation Hotstart= 0
Write HDF5 File= 1
Write Binary Output= 1
Write DSS Sediment File= 0
DSS Sediment Output Type= 1
SV Curve= 0
Specific Gage Flag= 0
Subcell Erosion Methods= 0
Subcell Deposition Methods= 0
Advection Scheme= 1
Matrix Solver= 0
Implicit Weighting Factor= 1
Maximum Outer Loop Convergence Iterations= 5
Convergence Maximum Absolute= 0.001
Convergence RMSE= 0.0001
Grain Fractions Max Abs Error= 0.001
Max Subgrid Regions= 1
Max Subgrid Length Scale= 3.402823E+38
Initial Layer Thickness= 3
Min Layer Thickness= 0.1
Max Layer Thickness= 6
Number of Layers= 5

--- CoonRn.f01 (steady flow) ---

Flow Title=Flow
Program Version=6.60
Number of Profiles= 1
Profile Names=P100yr
River Rch & RM=CoonRn,Main,19334
    1270
River Rch & RM=CoonRn,Main,11735
    1480
River Rch & RM=CoonRn,Main,6152
    1660
Boundary for River Rch & Prof#=CoonRn,Main            , 1
Up Type= 0
Dn Type= 3
Dn Slope=0.016695
DSS Import GetInterval= 0
DSS Import GetPeak= 0
DSS Import FillOption= 0

--- CoonRn.g01 (geometry) ---

Geom Title=Geometry
Program Version=6.60

River Reach=CoonRn          ,Main
Reach XY= 30
     1597841.429       459856.53      1597558.42      460251.012
     1597611.713       460688.32     1597299.141      460731.524
      1597243.48      461158.489     1596650.238      461582.636
     1596467.052      462223.0841596226.34853711462367.890943372
       1595702.6      463104.493      1595727.26      463861.898
     1595439.446      464150.857     1595389.907        464580.2
     1595176.336      464572.494     1595049.132      464754.721
     1595191.748      465570.993     1594697.453      466590.408
1594919.75988263466960.046866409     1594617.089      467352.217
     1595317.248      468668.869     1595436.694      469437.627
     1595666.227      469812.683     1595976.676      470090.105
     1596486.075      470032.4631596780.56342925470313.986966426
1596954.25208832470739.3726529931596805.47519373470970.401396417
     1597019.444      471350.556     1596949.325      472256.511
     1596524.788      473158.198     1594345.332      473597.596

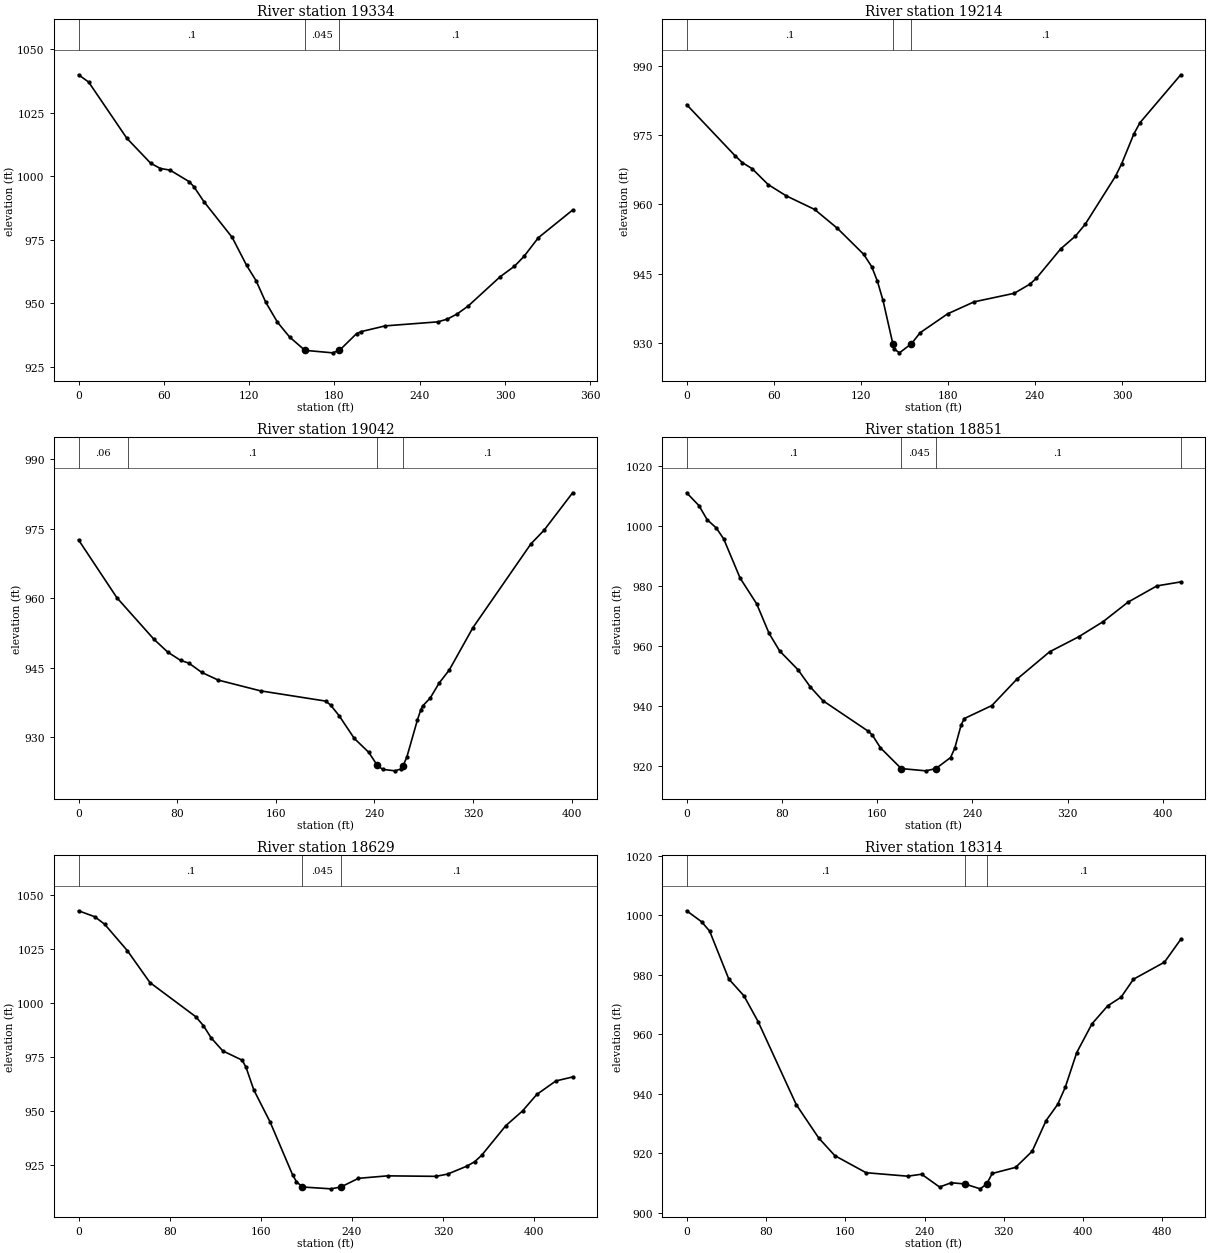
Type RM Length L Ch R = 1 ,19334   ,123.7,119.8,111
XS GIS Cut Line= 2
1597788.51445273459695.3731182381597866.33892034460034.126949186
#Sta/Elev= 30
       0 1039.95     7.1 1037.08      34 1014.95    50.8 1005.12    57.6 1003.07
    64.3 1002.46    77.8  997.91    81.1  995.95    88.2  990.04   108.1  975.96
   118.2  964.99   124.9  958.94   131.6  950.56   139.9  942.63   148.5  936.76
  159.25931.5364   178.7  930.55  183.56931.5361   195.6  938.12   198.9  938.91
   215.8  941.16   252.8  942.74   259.5  943.83   266.3  945.83   274.1  948.96
   296.6  960.49   306.7  964.63   313.4  968.51   323.5  975.85   347.6  986.73
#Mann= 3 ,-1,0
       0      .1       0  159.25    .045       0  183.56      .1       0
Bank Sta=159.25,183.56
XS Rating Curve= 0 ,0
Exp/Cntr(USF)=0,0
Exp/Cntr=0.3,0.1

Type RM Length L Ch R = 1 ,19214   ,167.8,171.5,170.4
XS GIS Cut Line= 3
1597603.26964217459832.1942516731597791.56474362459955.699640794
1597863.44083073460045.797834497
#Sta/Elev= 30
       0  981.68    33.3   970.6    38.3   969.1    45.1  967.77    56.2  964.31
    68.6  961.87    88.2  958.91   103.9   954.8     122  949.16   127.5  946.49
   131.4  943.36   135.3  939.15  142.07929.7261   143.2  928.57   146.6  927.77
   154.9  929.75   160.8  932.12   179.8  936.24   198.1  938.85   225.7   940.7
   236.5  942.69   240.9  943.95   257.7  950.35   267.8  953.11   274.5  955.65
   295.5  966.14   299.7  968.83   308.1  975.29   312.3  977.74   340.4  988.16
#Mann= 3 ,-1,0
       0      .1       0  142.07    .045       0   154.9      .1       0
Bank Sta=142.07,154.9
XS Rating Curve= 0 ,0
Exp/Cntr(USF)=0,0
Exp/Cntr=0.3,0.1

Type RM Length L Ch R = 1 ,19042   ,197.1,191.6,189.3
XS GIS Cut Line= 3
1597580.99817856459859.527411561 1597638.7015161460044.785495242
1597814.84854649460153.105795537
#Sta/Elev= 30
       0  972.55    31.1  960.09    61.1  951.15    72.4  948.36    82.7   946.6
    89.6  945.98    99.9     944   113.3  942.34   147.6  940.02   200.5  937.81
   204.4  936.97   211.4  934.66   223.6  929.79   235.4  926.77   242.4  923.94
   246.7   923.1   256.7  922.78   261.5  923.18  263.27923.8865   266.3  925.74
   274.9  933.75   277.6  935.92   279.2  936.77   285.3  938.48   292.5   941.7
   300.7   944.5   319.9  953.63   366.9  971.68   377.7  974.66   400.8  982.71
#Mann= 4 ,-1,0
       0     .06       0      40      .1       0   242.4    .045       0
  263.27      .1       0
Bank Sta=242.4,263.27
XS Rating Curve= 0 ,0
Exp/Cntr(USF)=0,0
Exp/Cntr=0.3,0.1

Type RM Length L Ch R = 1 ,18851   ,234.5,221.4,216.1
XS GIS Cut Line= 2
1597381.87258373460150.9635610671597774.68424001 460284.77920334
#Sta/Elev= 30
       0 1011.16    10.3 1006.89    17.2 1002.18    24.9   999.4    31.1  995.76
    44.9  982.66    58.8  974.06    69.2  964.21    78.1  958.31    93.5  952.03
   103.9  946.27   114.3  941.72   152.4  931.51   155.9  930.24   162.8  925.92
  180.26918.9854   200.9  918.23  209.34 918.986   221.7  922.68   225.2  925.79
   230.6  933.61   233.2   935.7   256.4  940.06   277.2  948.79   304.9  958.02
   329.2  963.01   349.9  968.11   370.7   974.6     395  980.04     415  981.37
#Mann= 4 ,-1,0
       0      .1       0  180.26    .045       0  209.34      .1       0
  414.98     .06       0
Bank Sta=180.26,209.34
XS Rating Curve= 0 ,0
Exp/Cntr(USF)=0,0
Exp/Cntr=0.3,0.1

Type RM Length L Ch R = 1 ,18629   ,294.5,315.5,324.5
XS GIS Cut Line= 6
1597346.08798434460447.9767115861597441.05268942460463.521956086
1597513.36848967460443.6361690911597609.78890051460417.121130258
1597682.10470076460397.2353432631597766.47264226460374.034274176
#Sta/Elev= 30
       0 1042.85    14.3 1040.07    22.9  1036.6    42.8 1024.36    62.7 1009.52
   102.8  993.72   109.6  989.55   116.4  983.85   126.6  977.82   143.6  973.51
     147  970.22   153.8  959.74   168.2  944.75   187.9  920.26   191.3   917.1
  196.53914.6448   221.6  913.79  230.27914.6472   245.7  918.67   271.2  919.82
   313.8  919.59     324  920.64     341  924.35   347.8  926.41   353.9  929.39
     375  943.09   389.7  949.93   402.2  957.58     419  963.87   433.7  965.71
#Mann= 3 ,-1,0
       0      .1       0  196.53    .045       0  230.27      .1       0
Bank Sta=196.53,230.27
XS Rating Curve= 0 ,0
Exp/Cntr(USF)=0,0
Exp/Cntr=0.3,0.1

Type RM Length L Ch R = 1 ,18314   ,260.3,270.8,267.4
XS GIS Cut Line= 5
1597353.28715286460514.4167764141597462.18686945460594.717796917
 1597538.2094546460651.0556466871597592.08774622460730.775758541
1597682.36036028460877.649571535
#Sta/Elev= 30
       0 1001.48      15  997.82    23.2  994.66    42.5  978.58    57.8  972.92
    72.1  964.26   110.6  936.38   133.2   925.2   149.5  919.25     181  913.52
     223  912.35   237.1  913.01   255.2  908.71   266.9  910.14   280.6  909.75
   296.2   908.1  302.75909.7464   308.3  913.26   331.9  915.31   348.6  920.71
   362.7  931.04   374.3  936.43     382  942.19   393.6  953.88     409  963.52
   424.9  969.58   438.3  972.45   450.8  978.49   482.1  984.22   498.5  991.86
#Mann= 3 ,-1,0
       0      .1       0   280.6    .045       0  302.75      .1       0
Bank Sta=280.6,302.75
XS Rating Curve= 0 ,0
Exp/Cntr(USF)=0,0
Exp/Cntr=0.3,0.1

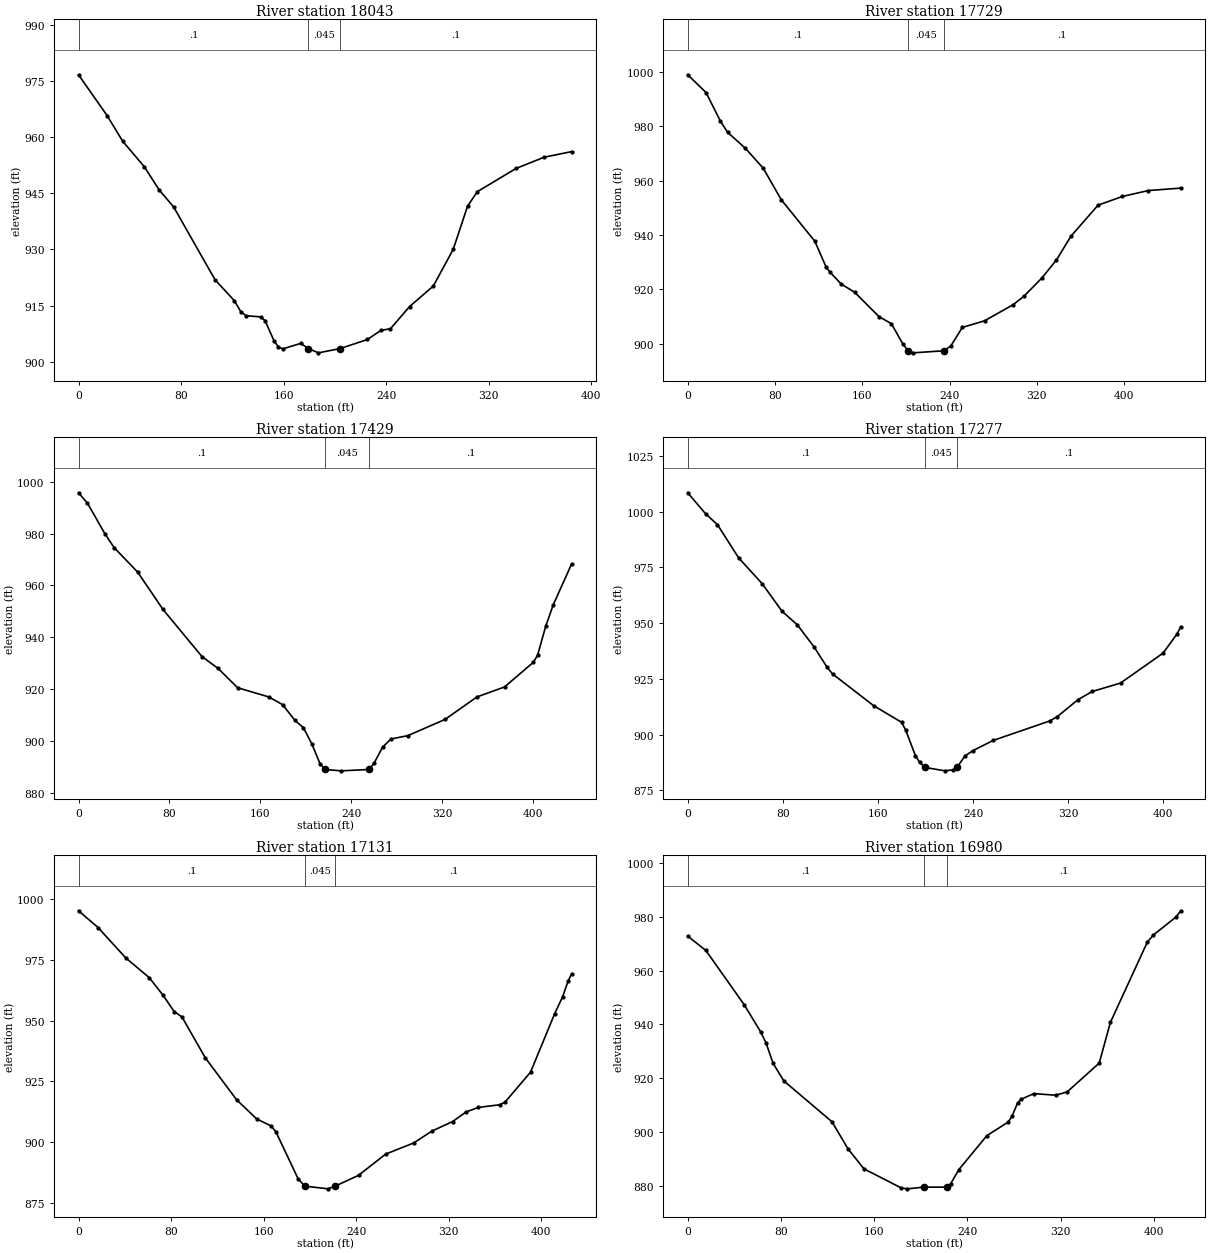
Type RM Length L Ch R = 1 ,18043   ,328.6,313.7,282.9
XS GIS Cut Line= 4
1597240.55936296460563.3906363251597320.11526726460676.042528421
1597352.29236826460769.6839772181597425.13530622460897.997090037
#Sta/Elev= 30
       0  976.59    22.5  965.61    34.4  958.89    51.4  952.02    62.8  945.92
    74.2  941.33   106.5   921.9   121.4  916.38   126.6  913.38   130.6  912.33
     142  912.01   145.5  911.01   152.4  905.67   155.9  903.97   159.4  903.49
   173.3  904.94179.1723 903.566   187.1  902.42204.0123 903.557   225.3  905.98
   235.7  908.39   243.3  908.86   258.2  914.77   276.7  920.24   292.2  930.02
   303.4  941.55     311  945.41   341.2   951.6   363.1   954.6   384.5  956.09
#Mann= 3 ,-1,0
       0      .1       0179.1723    .045       0204.0123      .1       0
Bank Sta=179.1723,204.0123
XS Rating Curve= 0 ,0
Exp/Cntr(USF)=0,0
Exp/Cntr=0.3,0.1

Type RM Length L Ch R = 1 ,17729   ,285.5,300,336.2
XS GIS Cut Line= 6
 1597017.2664635  461003.75479951597110.44180208461009.008397922
1597181.58962567460985.2794427571597276.32368818460953.256869003
  1597354.925237460959.1439963431597451.88042368460998.722985417
#Sta/Elev= 30
       0  998.91    16.8  992.38    29.9  981.91    36.5  977.78    52.9  971.86
    69.3  964.49    85.8  952.92   116.5   937.7   126.9  928.13   130.3  926.38
   140.7  921.93     153  918.93   175.3  909.96   186.7  907.36     197  900.04
  201.94897.3927   206.5  896.64  234.71897.3925   241.1  899.14   251.7  905.99
   272.1  908.43   298.4  914.38   308.3  917.51   324.7  924.21   337.9  930.76
   351.3  939.57   376.1  950.95   398.3  954.15   422.2  956.33   451.9  957.23
#Mann= 3 ,-1,0
       0      .1       0  201.94    .045       0  234.71      .1       0
Bank Sta=201.94,234.71
XS Rating Curve= 0 ,0
Exp/Cntr(USF)=0,0
Exp/Cntr=0.3,0.1

Type RM Length L Ch R = 1 ,17429   ,152.8,152.2,148.6
XS GIS Cut Line= 6
1597004.45087235461050.8820018321597084.81094784461103.262802586
1597128.75606993461164.8814457511597173.47710909 461254.32418026
1597207.01772442461321.4063951671597248.34572576461398.570282832
#Sta/Elev= 30
       0  995.71     7.9  991.69    23.5  979.71    31.4  974.55      52  965.18
    74.4  950.72   108.8  932.53   122.9  928.01   140.1  920.56   167.6  917.01
   179.7  914.04   190.6  907.95     198  905.16   205.3  899.03   212.6  891.32
  217.03889.0529     231  888.53  256.04889.0515   260.2  891.48   267.7  897.61
     275   900.8   289.9  902.09   322.7  908.35   350.8  917.02   375.1  920.86
   400.5   930.4   404.2  933.12   411.4  944.33   417.9  952.44   434.1  968.22
#Mann= 3 ,-1,0
       0      .1       0  217.03    .045       0  256.04      .1       0
Bank Sta=217.03,256.04
XS Rating Curve= 0 ,0
Exp/Cntr(USF)=0,0
Exp/Cntr=0.3,0.1

Type RM Length L Ch R = 1 ,17277   ,147.7,146.7,146.4
XS GIS Cut Line= 2
1596906.78023467461120.2272305651597139.61826334461463.297755901
#Sta/Elev= 30
       0 1008.48    15.1  999.02      25   994.2    42.8  979.29    62.8  967.58
    79.3  955.32    92.2   949.2   106.3   939.3   117.1  930.25   121.8   927.2
   156.4  912.93   179.8  905.52   183.2  902.12   191.5  890.51     195  887.52
  199.45885.2667   216.3  883.72   223.4  884.21   226.5  885.31   233.1  890.38
   239.9  892.81   256.9  897.36   304.5  906.12   310.8  908.06   328.3   915.7
   340.2  919.32     364  923.12   399.7  936.53   411.6  945.23   414.6  948.39
#Mann= 3 ,-1,0
       0      .1       0  199.45    .045       0   226.5      .1       0
Bank Sta=199.45,226.5
XS Rating Curve= 0 ,0
Exp/Cntr(USF)=0,0
Exp/Cntr=0.3,0.1

Type RM Length L Ch R = 1 ,17131   ,153,150.7,148.9
XS GIS Cut Line= 6
1596777.86175859461204.4998048391596829.09229918461275.434046179
1596873.00428484461336.2351056781596933.42312726461415.952465922
1596984.62249993461471.4900844991597045.84055334461535.211413756
#Sta/Elev= 30
       0   995.1    16.9  988.23    40.9  975.73    61.2  967.63    73.2  960.37
    82.7  953.73    89.5  951.49   109.7  934.68   136.7  917.51   154.2  909.58
   166.4   906.8   170.6  904.46     190  884.96   195.7  882.04   215.8  880.92
  222.04882.0408   242.2  886.47   265.6  895.18   289.9  899.76   305.6  904.62
   323.5  908.55   335.2  912.49   345.9  914.36   364.1  915.44   368.7  916.44
   390.9  928.81   411.8  952.85   418.7  959.85   423.4  966.19   426.4  969.16
#Mann= 3 ,-1,0
       0      .1       0   195.7    .045       0  222.04      .1       0
Bank Sta=195.7,222.04
XS Rating Curve= 0 ,0
Exp/Cntr(USF)=0,0
Exp/Cntr=0.3,0.1

Type RM Length L Ch R = 1 ,16980   ,150.7,150.5,147
XS GIS Cut Line= 2
1596646.94649253461335.0681169231596949.52344766461630.896143688
#Sta/Elev= 30
       0  972.76    15.6  967.42    48.4  947.37    62.5  937.33    67.2  933.16
    73.3  925.56    82.5  919.06   123.8  903.92   137.5  893.92   151.3  886.43
   183.4  879.35   188.6  879.03   202.5  879.67  222.56 879.666   225.7  880.91
   232.7  886.15   256.8  898.77   275.2  903.83   278.4  905.95   283.1  910.86
     286   912.2   297.1  914.35   315.9  913.75   325.7  914.99   353.2  925.66
   362.8  940.77   394.5  970.52   399.7  973.16   419.2  979.87   423.2  982.15
#Mann= 3 ,-1,0
       0      .1       0   202.5    .045       0  222.56      .1       0
Bank Sta=202.5,222.56
XS Rating Curve= 0 ,0
Exp/Cntr(USF)=0,0
Exp/Cntr=0.3,0.1

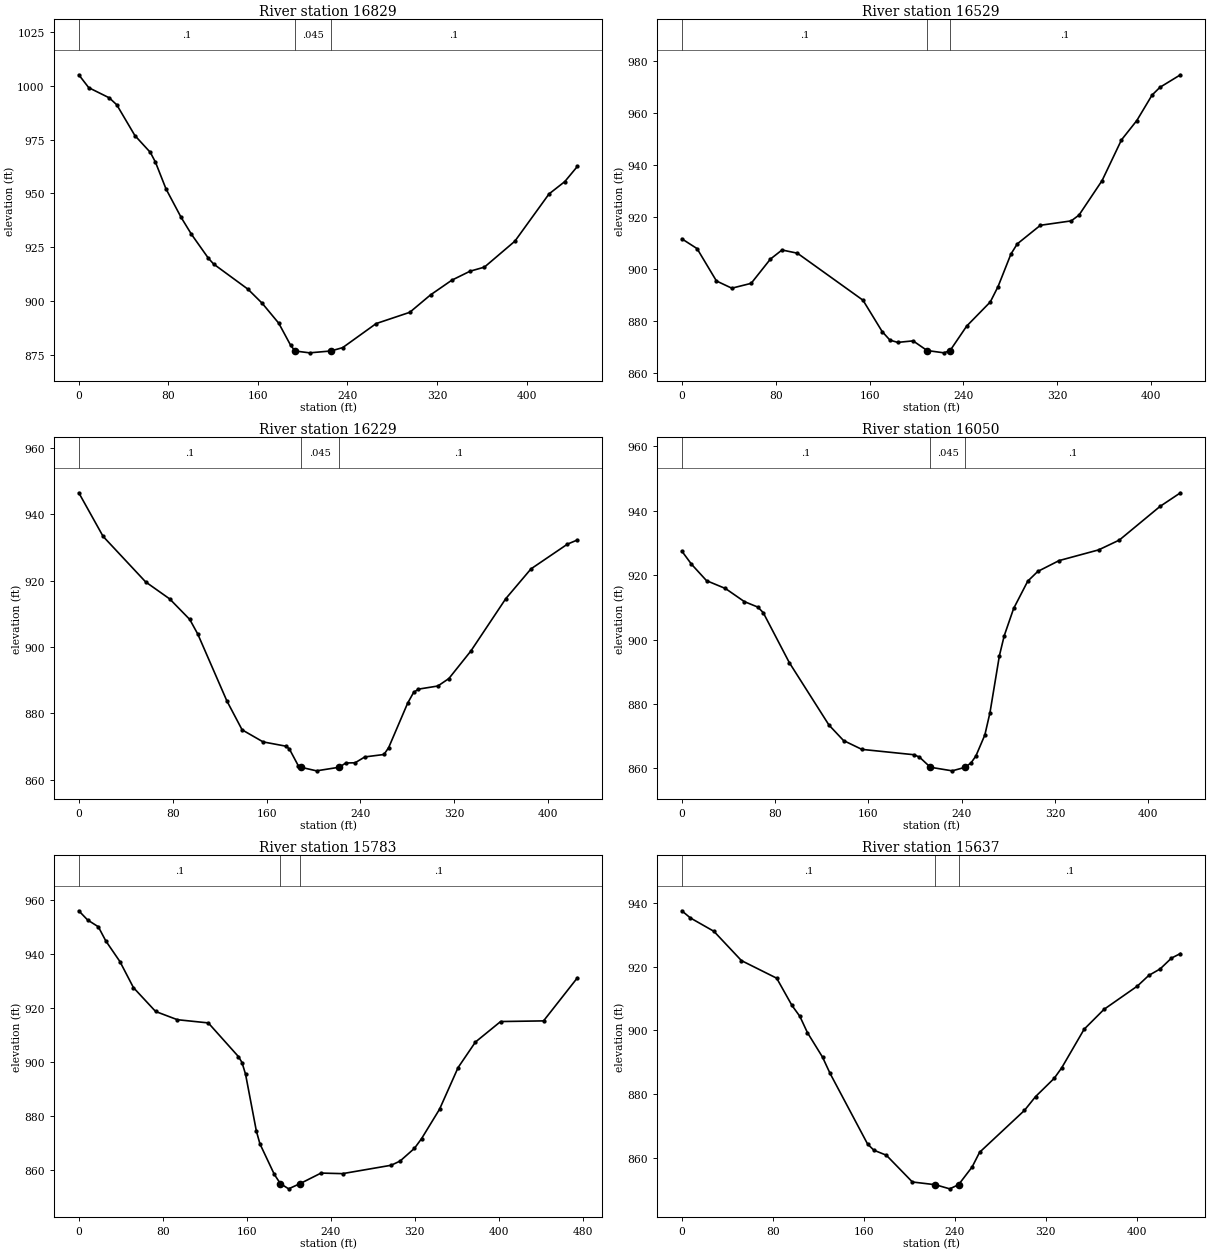
Type RM Length L Ch R = 1 ,16829   ,313.1,300,290.2
XS GIS Cut Line= 6
1596522.40032725461409.3986732511596584.99534643461470.538642839
1596638.64845434461522.9443779291596710.18571284461592.818581998
1596772.19313475461648.7489163431596852.63916808 461707.18088609
#Sta/Elev= 30
       0 1005.17     8.9  999.17    27.2  994.45    33.9  991.22    50.1  976.91
    63.9  969.08    68.5  964.51    77.9  952.09    91.4  938.86   100.6  931.01
   115.8  919.82   120.5  917.13   151.1  905.46   163.8  898.92   178.6  889.64
   189.3  879.29  193.16876.7205   206.1  875.86  225.12876.7188   235.7  878.28
   265.6  889.47   295.6   894.7   314.2  902.82   333.2  909.65   349.5  913.83
   362.3  915.72   389.5  927.78     420  949.75   434.1   955.5   445.4  962.59
#Mann= 3 ,-1,0
       0      .1       0  193.16    .045       0  225.12      .1       0
Bank Sta=193.16,225.12
XS Rating Curve= 0 ,0
Exp/Cntr(USF)=0,0
Exp/Cntr=0.3,0.1

Type RM Length L Ch R = 1 ,16529   ,294.1,300,307.5
XS GIS Cut Line= 6
1596417.32507809 461832.140609921596504.64839426461837.698013499
1596579.49699783 461842.461455421596679.29502659  461848.8121645
1596754.14363018461853.5752783421596841.46694633461859.132353842
#Sta/Elev= 30
       0   911.6      13  907.82    29.5  895.35    42.6  892.56    59.1  894.43
    75.5  903.78    85.4  907.29    98.5  906.05   154.4  887.93   170.8  875.81
   177.4  872.53     184  871.67   197.1  872.25  209.02868.5373   223.4  867.64
  228.68868.5365   242.8  877.96   262.9  887.25   269.5  893.16   280.5  905.73
   285.9  909.64   305.6  916.81   331.9  918.51   338.5  920.73   358.2  934.05
   374.7  949.73   387.8   957.2   400.8  967.02   407.5     970     425  974.83
#Mann= 3 ,-1,0
       0      .1       0  209.02    .045       0  228.68      .1       0
Bank Sta=209.02,228.68
XS Rating Curve= 0 ,0
Exp/Cntr(USF)=0,0
Exp/Cntr=0.3,0.1

Type RM Length L Ch R = 1 ,16229   ,173.3,179.4,182.4
XS GIS Cut Line= 6
1596347.96465251461994.9791949991596418.72927475462046.443987086
1596479.38466525462090.5564316661596560.25851926462149.373571262
1596620.91390976462193.4860158411596692.26941009462244.138145506
#Sta/Elev= 30
       0  946.52    20.7  933.37      57  919.62    77.5  914.49    94.6  908.29
   101.4   903.9   126.2  883.73   139.2     875   157.1  871.36   176.8  870.05
   179.5  869.21     187  864.23  189.23863.7144   202.6  862.63  221.92863.7148
   227.6     865   235.5  865.06   243.8  866.83   260.1  867.56   264.1  869.64
   280.3  883.06   285.4  886.31   289.5  887.28     306  888.22   315.4  890.47
   334.2   898.8   363.9  914.57   385.4  923.56   416.5  931.03     425  932.29
#Mann= 3 ,-1,0
       0      .1       0  189.23    .045       0  221.92      .1       0
Bank Sta=189.23,221.92
XS Rating Curve= 0 ,0
Exp/Cntr(USF)=0,0
Exp/Cntr=0.3,0.1

Type RM Length L Ch R = 1 ,16050   ,272.3,266.7,262.2
XS GIS Cut Line= 2
 1596290.9280577 462083.330913431596541.89123214 462429.65395392
#Sta/Elev= 30
       0  927.44     8.3  923.36    21.2  918.26    37.4  915.83    53.6  911.77
    65.2  910.06    69.8  908.35    92.2  892.83   126.2  873.46   138.7  868.65
   154.4  865.91   199.1  864.25   203.8  863.52   213.2  860.36   231.9  859.25
  243.12860.3655   248.1  861.74   252.2  863.84   259.9  870.37   264.3   877.3
   272.4     895   276.5  901.14   284.6  909.63   296.7  918.11   305.3  921.12
   323.6  924.49   357.5  927.81   375.3  930.87   410.2  941.31   427.7  945.53
#Mann= 3 ,-1,0
       0      .1       0   213.2    .045       0  243.12      .1       0
Bank Sta=213.2,243.12
XS Rating Curve= 0 ,0
Exp/Cntr(USF)=0,0
Exp/Cntr=0.3,0.1

Type RM Length L Ch R = 1 ,15783   ,150.2,146.8,144.8
XS GIS Cut Line= 2
1596012.20977959462345.6076577821596467.76244438462480.586225127
#Sta/Elev= 30
       0  955.96     8.4  952.56    18.6  950.05    25.7  944.84    39.2  937.17
    52.1  927.53    73.2  918.72    93.9  915.68   123.4  914.49   152.1  902.04
   155.5  899.85   158.9  895.49   169.2  874.47   172.6  869.75   186.3  858.47
     192   855.1   199.9  853.13  211.03   855.1   230.8  858.96   251.3  858.75
   297.6  861.85   306.1   863.4   319.8  868.11   326.6  871.71   343.7  882.57
   361.4  897.99   377.9  907.42   401.9     915   442.8  915.24   475.1   931.2
#Mann= 3 ,-1,0
       0      .1       0     192    .045       0  211.03      .1       0
Bank Sta=192,211.03
XS Rating Curve= 0 ,0
Exp/Cntr(USF)=0,0
Exp/Cntr=0.3,0.1

Type RM Length L Ch R = 1 ,15637   ,295.7,302,308.4
XS GIS Cut Line= 6
1595980.29117526 462509.369242341596072.31658176462539.476793677
 1596149.3177401462548.4269070031596249.31786817462548.426907003
1596324.31771818462548.4269070031596411.81754318 462564.94557476
#Sta/Elev= 30
       0  937.55     7.5  935.31    28.2  931.11    52.4  921.92    83.4   916.4
    96.8  907.87   103.8  904.42   110.4  899.34   123.7  891.64   130.3  886.55
   163.3  864.38   168.8  862.44   179.8  860.86   202.7  852.46  222.99851.5988
   235.5  850.31  243.26851.5983   255.2  857.16   261.8  861.78   301.2  874.91
     311  879.25   327.4  884.99     334  888.29   353.7  900.39   371.2  906.63
   400.5  913.93   410.5  917.26   420.5   919.3   430.5  922.71   438.4  924.14
#Mann= 3 ,-1,0
       0      .1       0  222.99    .045       0  243.26      .1       0
Bank Sta=222.99,243.26
XS Rating Curve= 0 ,0
Exp/Cntr(USF)=0,0
Exp/Cntr=0.3,0.1

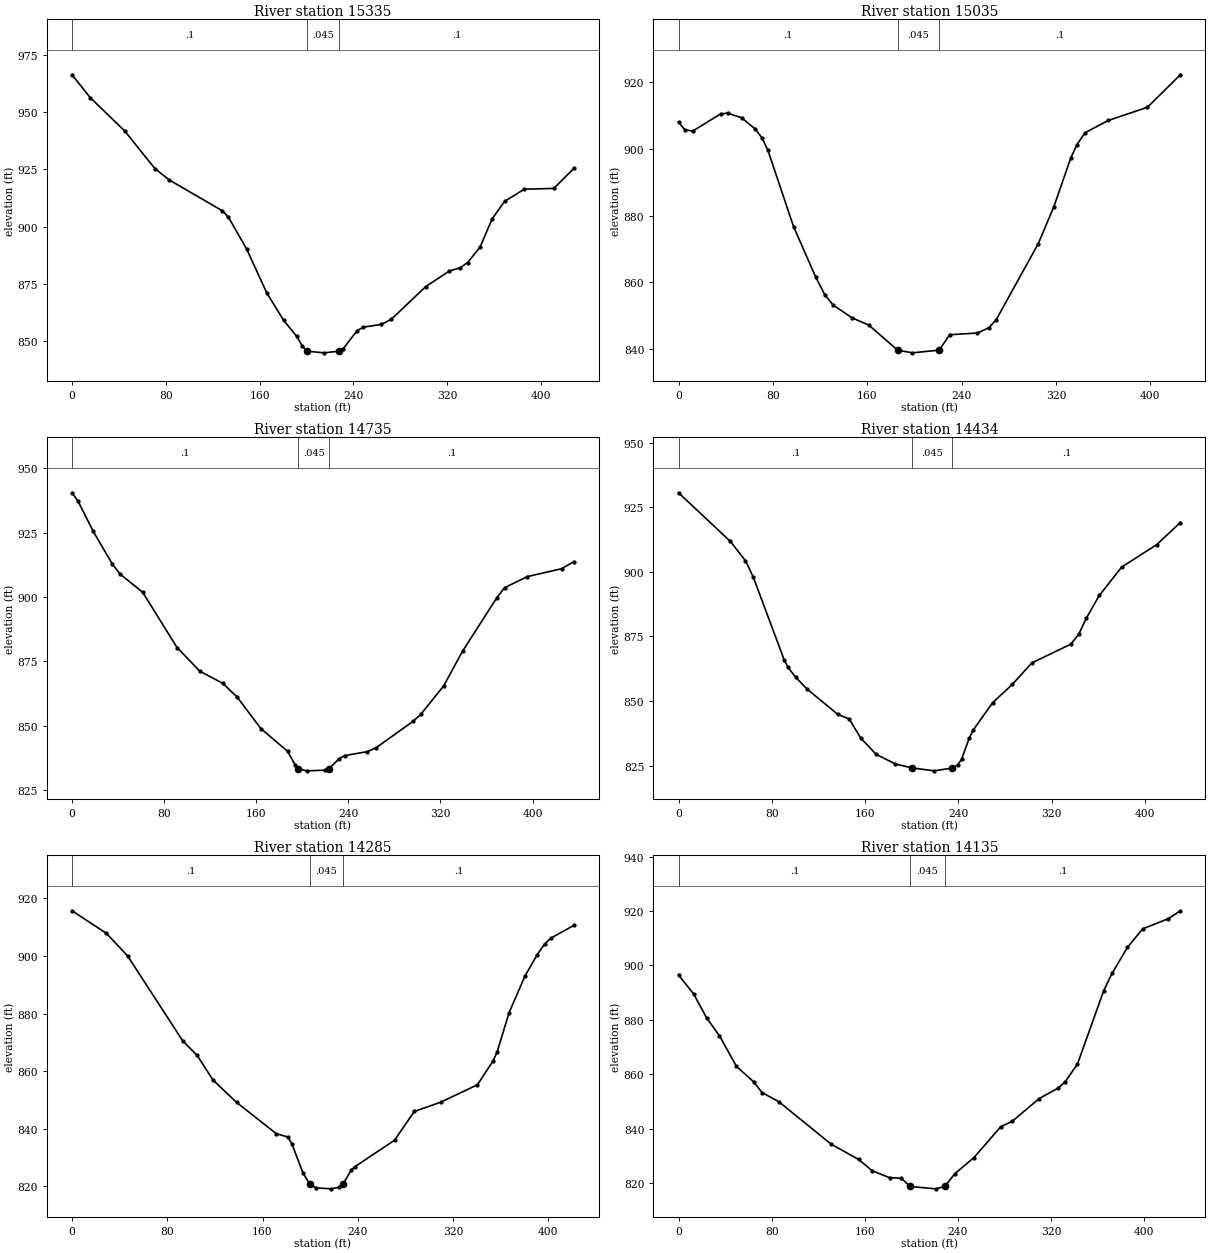
Type RM Length L Ch R = 1 ,15335   ,290.3,300,301.4
XS GIS Cut Line= 6
 1595850.7294265462633.6872351771595918.88906708462688.555563763
1595977.31152242462735.5856534241596055.20802018 462798.29222092
1596113.63080359462845.3219825031596184.55421817462901.697525918
#Sta/Elev= 30
       0  966.45    15.4   956.5    44.9  941.86    70.6  925.42    82.8  920.44
   128.1  906.95   133.4  904.13   149.1  890.01     166  871.09   180.5  858.95
   191.7  851.92   196.5  847.65  200.28845.4752     215  844.73     228845.4733
   231.4  846.58   243.2  854.45   248.5  855.98   263.9  857.18   272.4  859.43
   301.8  873.76   321.7   880.5   331.3  882.03   337.4  884.24     348  890.93
   358.5  903.47     369  911.02   385.8  916.36     411   916.7   428.1  925.47
#Mann= 3 ,-1,0
       0      .1       0  200.28    .045       0     228      .1       0
Bank Sta=200.28,228
XS Rating Curve= 0 ,0
Exp/Cntr(USF)=0,0
Exp/Cntr=0.3,0.1

Type RM Length L Ch R = 1 ,15035   ,321.4,300,288.7
XS GIS Cut Line= 6
1595714.91506559462808.5753368441595763.67152976462881.232343748
1595805.46311285462943.5097782611595861.18511426463026.546357587
1595902.97604117463088.8241201791595955.01957226463159.789529428
#Sta/Elev= 30
       0  907.97     5.3  905.71    12.1  905.33    35.7  910.49    41.6  910.69
    53.4  909.33    65.1  905.92      71  903.15    75.8  899.55    97.5  876.72
   116.4   861.5     124  856.29   131.1  853.18   146.9   849.4   161.4  847.15
   185.8839.6643   198.3  838.86  221.08 839.664   229.9  844.28   253.5  844.81
     263  846.35   269.4  848.81     305  871.55   318.3   882.7   332.6  897.26
   337.8  901.24   344.7  904.83   364.5  908.52   397.6  912.46   425.5   922.2
#Mann= 3 ,-1,0
       0      .1       0   185.8    .045       0  221.08      .1       0
Bank Sta=185.8,221.08
XS Rating Curve= 0 ,0
Exp/Cntr(USF)=0,0
Exp/Cntr=0.3,0.1

Type RM Length L Ch R = 1 ,14735   ,294.8,301.1,307.6
XS GIS Cut Line= 6
1595477.02282484463250.7893474251595563.79922609463239.559383005
1595638.17899859463229.9337460851595737.35202859463217.099126086
1595811.73114492463207.4695521741595909.39728817463219.112245426
#Sta/Elev= 30
       0  940.51     5.2  937.23    18.4  925.51      35   912.8    41.7  908.96
    61.4  901.84    91.2  880.42   111.1   871.2   130.9  866.53   143.3  861.23
     164  848.96   187.2  840.14   193.8  834.82  196.68833.3102   203.7  832.54
     220   832.8  223.04833.3091   231.9  837.18   236.8  838.45   256.6  840.01
   264.1  841.51   296.3   851.8   302.9  854.46   322.8  865.53   339.3  879.07
   369.1  899.84   375.7  903.66   395.5  907.97   425.2  911.02   435.9  913.75
#Mann= 3 ,-1,0
       0      .1       0  196.68    .045       0  223.04      .1       0
Bank Sta=196.68,223.04
XS Rating Curve= 0 ,0
Exp/Cntr(USF)=0,0
Exp/Cntr=0.3,0.1

Type RM Length L Ch R = 1 ,14434   ,149.5,148.9,148.2
XS GIS Cut Line= 6
1595565.80775225463505.9016980831595656.25081284463498.389574006
1595733.20899226463496.4479768431595831.59495033463514.480093002
1595905.04723126463529.6372149291595990.74194175463547.320250422
#Sta/Elev= 30
       0  930.69    44.5  911.83    57.4  904.37    64.2  897.89    90.6  865.92
    93.8  863.07   100.4  859.22   110.3  854.59   136.5  844.86   146.4  843.01
   156.2  835.66   169.4  829.35     186  825.59  200.44824.0544   219.4  822.94
  234.81824.0538   239.4  825.25   242.7  827.43   249.4  835.72   252.7  838.75
   269.4  849.37   286.2  856.42   302.9  864.75   336.4  872.03   343.1   875.8
   349.8  882.16   360.8  890.89     380  901.88   410.1  910.61   430.3  919.16
#Mann= 3 ,-1,0
       0      .1       0  200.44    .045       0  234.81      .1       0
Bank Sta=200.44,234.81
XS Rating Curve= 0 ,0
Exp/Cntr(USF)=0,0
Exp/Cntr=0.3,0.1

Type RM Length L Ch R = 1 ,14285   ,151.6,150,149.9
XS GIS Cut Line= 2
1595548.78336504463621.2676013341595965.86713814463683.020295894
#Sta/Elev= 30
       0  915.71    28.9  907.86    46.7  900.01    92.9  870.58   105.1  865.47
   118.4  856.93   138.3  849.12   171.5  838.32   181.4   837.1   184.7  834.75
     194  824.65  199.58820.8866   204.6  819.48   217.9  819.13   224.5  819.71
   227.8  820.89   234.5  825.61   237.4  826.76     271  836.04   287.5     846
   309.6  849.21   340.6  855.27   353.9   863.7   357.2  866.77   367.1  880.23
   380.4  892.94   390.5  900.27     397  904.16     402  906.13   421.6  910.65
#Mann= 3 ,-1,0
       0      .1       0  199.58    .045       0   227.8      .1       0
Bank Sta=199.58,227.8
XS Rating Curve= 0 ,0
Exp/Cntr(USF)=0,0
Exp/Cntr=0.3,0.1

Type RM Length L Ch R = 1 ,14135   ,284.2,300,306.3
XS GIS Cut Line= 6
1595526.15822525463735.4560290131595609.17085451463776.839148343
1595682.77241334463795.4070245921595782.34636118463804.626822427
1595857.02698609463811.5418348461595944.15410842463819.609404013
#Sta/Elev= 30
       0   896.5    13.2  889.38    24.2  880.67    35.2  874.15    49.8  862.88
    64.5  857.28    71.8   853.3    86.3   849.9     131  834.39   154.7  828.73
   166.6  824.52   181.4  822.04   191.3  821.82  199.02 818.804   220.9  817.93
  228.73818.8043   237.4  823.47   253.9  829.44   276.9  840.75   286.8  842.76
   309.9   851.1   326.2  854.93   332.3  857.29   342.8  863.77   365.4  890.77
   372.5  897.04   385.7   906.6   398.8  913.43   420.9  917.16   431.2  920.08
#Mann= 3 ,-1,0
       0      .1       0  199.02    .045       0  228.73      .1       0
Bank Sta=199.02,228.73
XS Rating Curve= 0 ,0
Exp/Cntr(USF)=0,0
Exp/Cntr=0.3,0.1

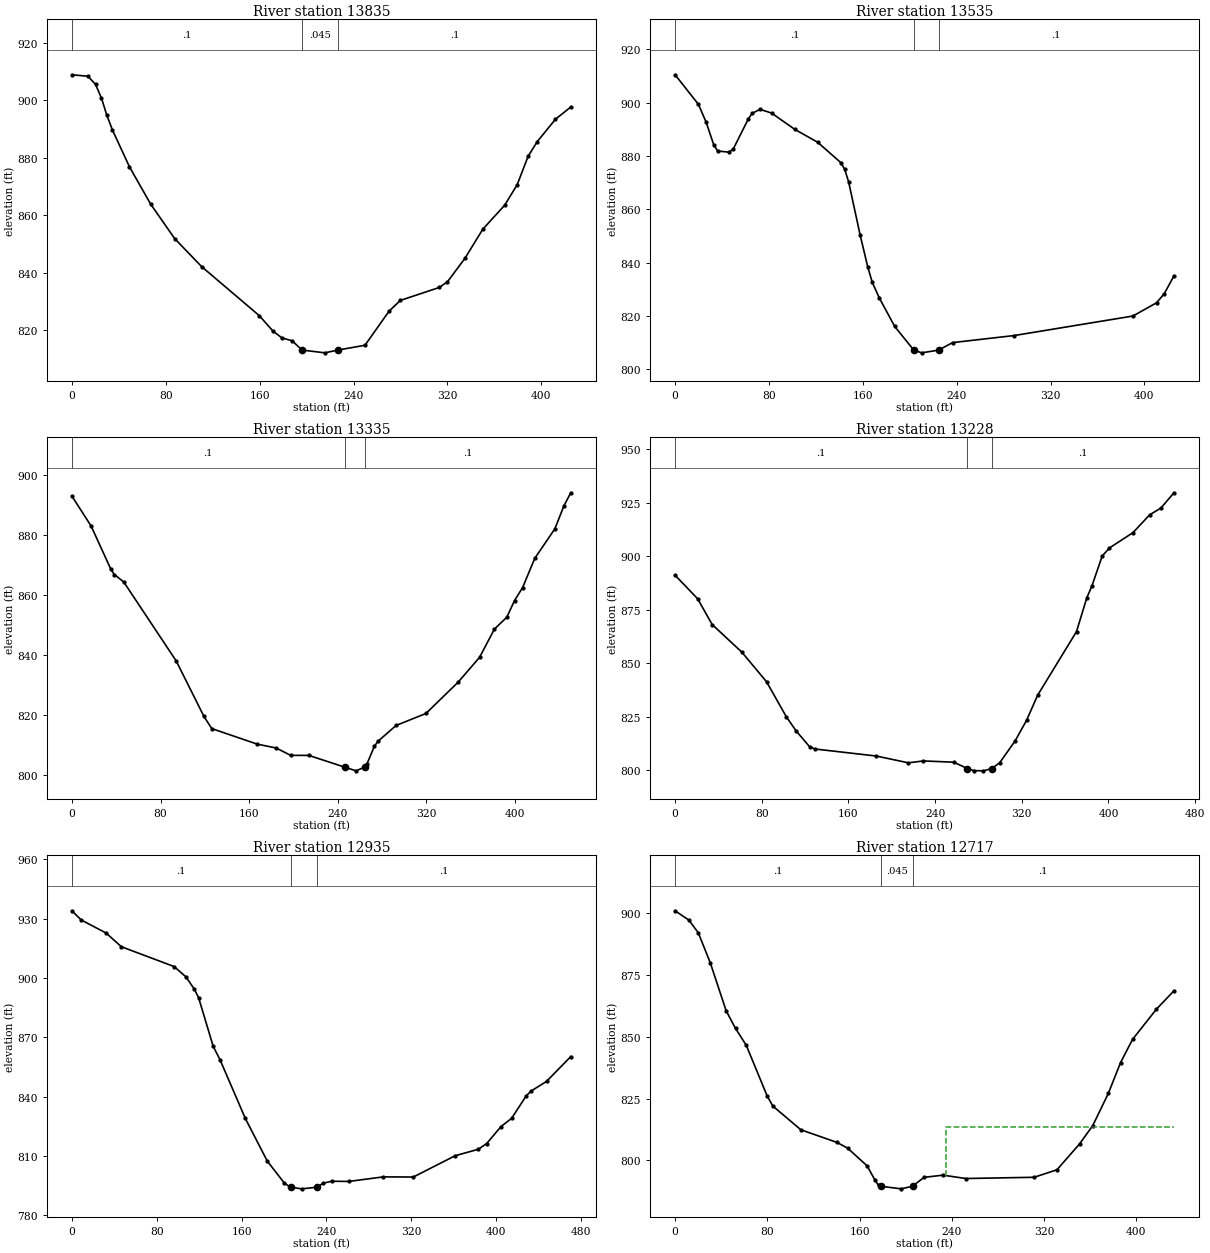
Type RM Length L Ch R = 1 ,13835   ,310.1,300,288.7
XS GIS Cut Line= 6
1595396.30776317463846.9948479241595455.96643651463911.003250092
1595507.10248908463965.8676416721595575.28345509464039.020382509
1595626.47003251464093.8381862491595688.29635242464155.825923175
#Sta/Elev= 30
       0  908.91    13.6   908.4    20.1  905.58    25.2  900.76    29.7  894.87
    34.5  889.72      49   876.9      67  863.95    87.5  851.92   110.6  842.12
   159.8  825.03   171.4  819.66   178.9  817.35   187.7  816.32  195.99 813.121
   215.5  812.14  226.79813.1218   249.7  814.78   270.3  826.69   279.9  830.39
     313  834.89     320  836.88   334.9  845.06   350.1  855.18   368.7  863.51
   379.4  870.67   388.7  880.56   396.5  885.66   411.9   893.4     425  897.69
#Mann= 3 ,-1,0
       0      .1       0  195.99    .045       0  226.79      .1       0
Bank Sta=195.99,226.79
XS Rating Curve= 0 ,0
Exp/Cntr(USF)=0,0
Exp/Cntr=0.3,0.1

Type RM Length L Ch R = 1 ,13535   ,200,200.1,200.8
XS GIS Cut Line= 6
1595203.11129917464269.5783203391595290.59570426464267.932982415
1595365.58243093464266.5218960051595465.56484251464264.640009999
1595540.55156918 464263.22859551 1595628.1353835464266.855884835
#Sta/Elev= 30
       0  910.51    19.9   899.4    26.5  892.65      33  884.14    36.3  881.89
    45.7  881.48    49.4  882.51    62.5  894.02    65.8  896.08    72.4  897.53
    82.2  896.15   101.9  890.05   121.6  885.16   141.3  877.52   144.6  874.96
   147.9  870.35   157.7  850.41   164.3  838.24   168.1  832.56   174.1  826.71
   187.2  816.05  203.45807.1755   210.2  806.15  224.59807.1718   236.5  809.99
     289  812.64   390.3  819.97   410.4  824.94     417  828.37   425.2  835.02
#Mann= 3 ,-1,0
       0      .1       0  203.45    .045       0  224.59      .1       0
Bank Sta=203.45,224.59
XS Rating Curve= 0 ,0
Exp/Cntr(USF)=0,0
Exp/Cntr=0.3,0.1

Type RM Length L Ch R = 1 ,13335   ,97.1,106.1,113.3
XS GIS Cut Line= 4
1595209.54414313464351.1537942031595348.83472337464463.417843946
 1595482.9278939464467.575771715  1595606.626245464526.826242413
#Sta/Elev= 30
       0  892.91    17.3  882.97    35.2  868.52    38.3  866.81    46.8  864.31
    94.1  838.03   119.2  819.52   126.2  815.49   167.3  810.31   184.3  809.03
   197.4  806.58   213.8  806.56  246.19802.6515   256.5  801.42  264.08 802.653
   266.4  803.82   272.9  809.54   276.2  811.25   292.6  816.54   319.5  820.52
   348.6  830.96   367.9  839.22   381.3  848.61   392.5  852.58   399.5  858.15
   406.8  862.47   417.7  872.17   435.9  882.04   444.1  889.72   450.2  894.03
#Mann= 3 ,-1,0
       0      .1       0  246.19    .045       0  264.08      .1       0
Bank Sta=246.19,264.08
XS Rating Curve= 0 ,0
Exp/Cntr(USF)=0,0
Exp/Cntr=0.3,0.1

Type RM Length L Ch R = 1 ,13228   ,285.7,293.8,286.8
XS GIS Cut Line= 2
1595202.56766509464362.4341057541595521.49206317464694.481752456
#Sta/Elev= 30
       0  891.07    20.8  880.09    34.2  868.06    61.7  855.09    84.4  841.32
   102.6     825   111.7  818.37   124.2  810.93     129  809.92   185.8  806.62
   215.3  803.45   229.2  804.34   257.1  803.75  269.78800.7907   275.6  799.82
   284.6  799.71  292.28800.7908   299.5  803.44   313.7  813.59   324.4  823.31
   334.6  835.03   370.5  864.78     380  880.57   384.7  886.09   394.2  900.06
   400.9  903.84   422.6  910.99   438.1  919.35   448.4  922.48   460.4  929.61
#Mann= 3 ,-1,0
       0      .1       0  269.78    .045       0  292.28      .1       0
Bank Sta=269.78,292.28
XS Rating Curve= 0 ,0
Exp/Cntr(USF)=0,0
Exp/Cntr=0.3,0.1

Type RM Length L Ch R = 1 ,12935   ,225,217.8,202.2
XS GIS Cut Line= 6
1595002.57462676464434.7617170071595053.80483925464505.695958346
1595097.71649684464566.4973459241595156.26395193 464647.56608142
1595203.46956617 464712.54528217 1595296.4510075 464799.81708926
#Sta/Elev= 30
       0  933.96     8.7  929.32    32.2  922.73    46.6   915.8    96.3  905.79
   107.5  900.58   115.4  894.37   119.5  889.94   133.2  865.46   139.7  858.61
   163.5  829.01   184.2  807.46   200.4  796.29  206.12794.2777   216.6  793.45
  231.15794.2786   236.8  796.29   244.9  797.29   261.1  797.19   293.5  799.49
   321.9  799.42   361.3  810.18   383.1  813.43   391.1  816.36   404.4  824.83
   414.6  829.11   428.2  840.33   432.6  842.76   447.5  847.75   470.3  860.26
#Mann= 3 ,-1,0
       0      .1       0  206.12    .045       0  231.15      .1       0
Bank Sta=206.12,231.15
XS Rating Curve= 0 ,0
Exp/Cntr(USF)=0,0
Exp/Cntr=0.3,0.1

Type RM Length L Ch R = 1 ,12717   ,147,142.3,135.8
XS GIS Cut Line= 4
1594885.22577721464708.7355822741595008.92412831464798.131029292
1595185.63605847464812.6837764811595283.34736102464844.907716685
#Sta/Elev= 30
       0     901      12  897.21    20.1   892.1    30.5  879.95    44.3  860.48
    52.4  853.38    61.7  846.58    79.8   826.1    84.8  821.94   109.1  812.34
   140.1  807.29   149.6  804.93   166.6  797.73   173.2  792.13   176.5  789.81
  178.28 789.481   196.2  788.43     206789.4797     216  793.09   232.5  793.97
   252.2  792.61   311.5  793.11   331.3  796.14   350.9   806.6   362.4  814.07
   375.9  827.07   386.5  839.55   396.9  848.93   417.6  861.16   432.8  868.59
#Mann= 3 ,-1,0
       0      .1       0  178.28    .045       0     206      .1       0
#XS Ineff= 2 , 0
                          234.88           813.4
Permanent Ineff=
       F       F
Bank Sta=178.28,206
XS Rating Curve= 0 ,0
Exp/Cntr(USF)=0,0
Exp/Cntr=0.3,0.1