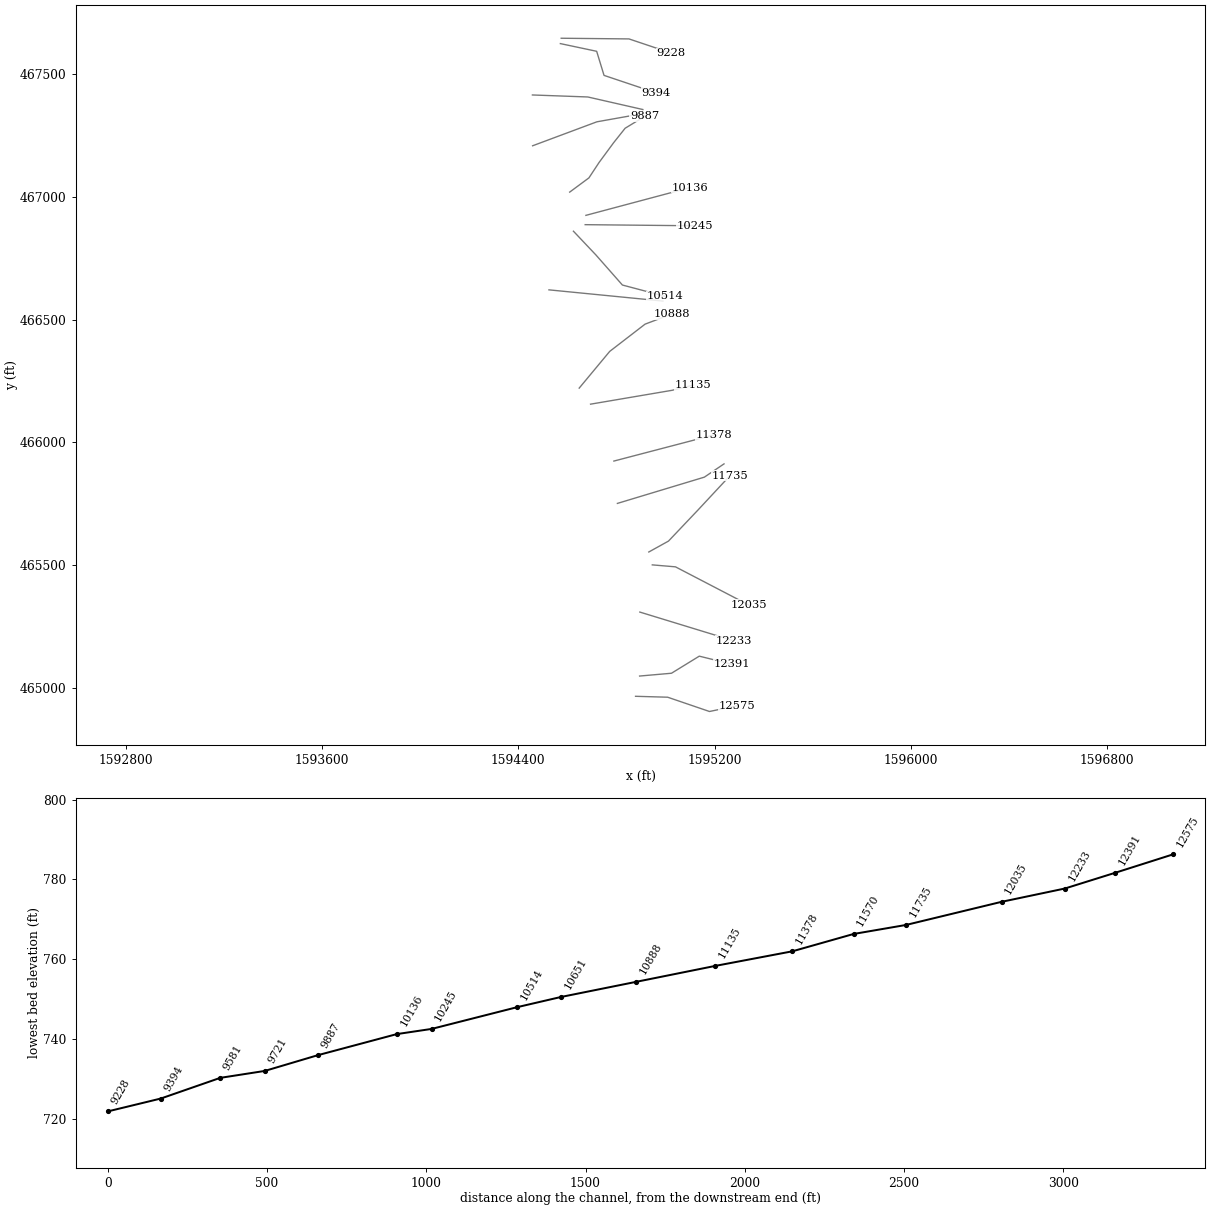
HEC-RAS study CoonRn.prj: CoonRn

--- CoonRn.g01 (geometry) --- (continued)

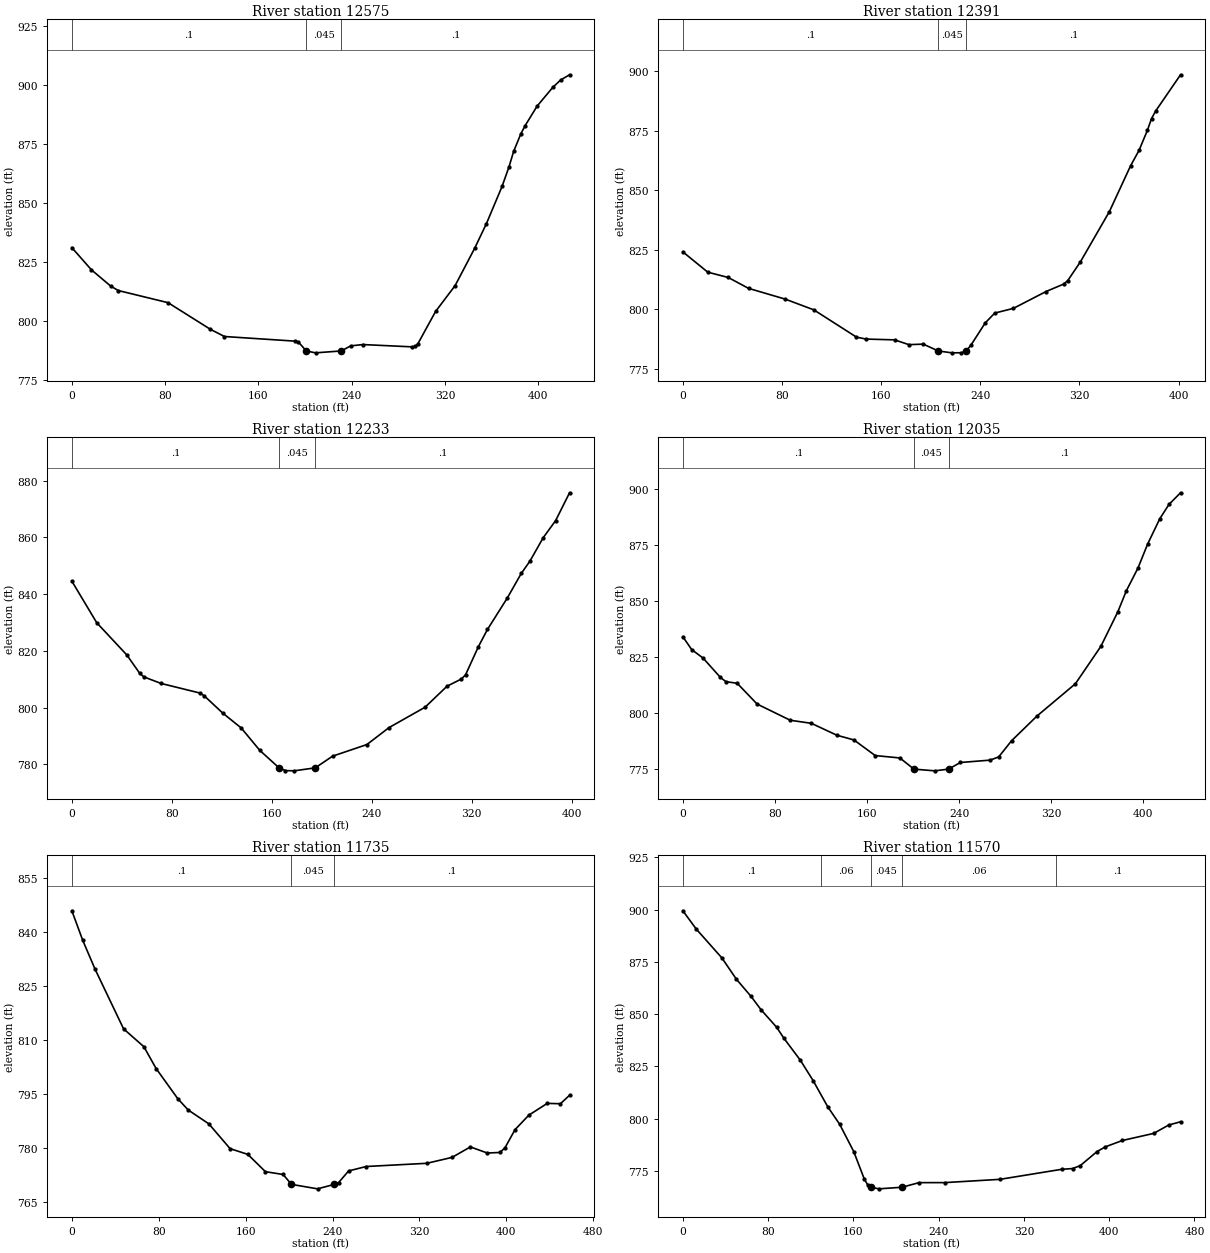
Type RM Length L Ch R = 1 ,12575   ,165,183.7,187.2
XS GIS Cut Line= 4
1594878.07638849464965.0678472071595008.92412831464961.329694197
1595179.39916681464903.1187054411595292.85295882464926.745729369
#Sta/Elev= 30
       0  830.91    16.8  821.49    33.3  814.61    39.8  812.73    82.5  807.58
   118.9  796.27   130.9  793.24   191.7  791.27   194.2  790.97  201.08 787.121
     209  786.32  231.02787.1194   239.2  789.27   249.6  789.83   291.7  788.86
   294.7  789.06   296.9  790.25     312  803.86   328.8  814.86   345.5  830.62
   355.6  841.08     369  856.83     375   865.2     379  871.76   385.2  879.22
   388.8   882.6   399.1   890.9   412.5  898.82   419.2  901.94   426.9  904.17
#Mann= 3 ,-1,0
       0      .1       0  201.08    .045       0  231.02      .1       0
Bank Sta=201.08,231.02
XS Rating Curve= 0 ,0
Exp/Cntr(USF)=0,0
Exp/Cntr=0.3,0.1

Type RM Length L Ch R = 1 ,12391   ,170.6,157.4,148.4
XS GIS Cut Line= 4
1594894.58111469465047.6066953881595024.51635744465059.040996751
1595137.81988913 465128.686286871595271.91305966465095.422864723
#Sta/Elev= 30
       0  824.08    20.1  815.55    36.6  813.32      53  808.75    82.7  804.21
   105.7  799.71   140.1  788.25   147.8  787.44   170.9   787.1   182.4  785.09
     194  785.31  206.09782.4421   217.1  781.65   224.8  781.69  228.62782.4426
   232.4  784.82     244  794.23   251.7  798.36   266.7  800.33   293.1  807.42
   307.3  810.55   310.6  812.02   320.8  819.88   344.2  841.01   361.3  860.26
   368.1  866.71   374.9   875.2   378.2  880.11   381.6  883.33   401.6   898.5
#Mann= 3 ,-1,0
       0      .1       0  206.09    .045       0  228.62      .1       0
Bank Sta=206.09,228.62
XS Rating Curve= 0 ,0
Exp/Cntr(USF)=0,0
Exp/Cntr=0.3,0.1

Type RM Length L Ch R = 1 ,12233   ,201.4,198.8,196
XS GIS Cut Line= 2
1594895.52665373465308.3656455621595276.34052865465191.877218816
#Sta/Elev= 30
       0  844.54    19.9   829.9      44  818.53    54.3  812.07    57.7   810.8
    71.4  808.51   102.3  805.15   105.7  804.24   120.7  798.07   135.5  792.83
   150.3  784.96  165.74778.7795   170.9  777.81   177.8  777.72  194.77778.7801
   208.6  782.89   236.1  786.99   253.7  792.94   282.6  800.13   300.2  807.55
   311.6  810.06     315  811.56   325.3  821.49   332.5  827.52   348.3  838.54
   359.6  847.29   366.5  851.61   377.2  859.91   387.1  865.91   398.2  875.69
#Mann= 3 ,-1,0
       0      .1       0  165.74    .045       0  194.77      .1       0
Bank Sta=165.74,194.77
XS Rating Curve= 0 ,0
Exp/Cntr(USF)=0,0
Exp/Cntr=0.3,0.1

Type RM Length L Ch R = 1 ,12035   ,276.7,300,321.3
XS GIS Cut Line= 6
1594946.27716717465500.7671309261595040.74777876465492.753039345
1595107.27651709465458.127124339 1595195.9810641465411.959237665
1595262.50947434465377.3333226741595340.12611701465336.936093763
#Sta/Elev= 30
       0  834.18     7.7  828.45    17.6  824.66    32.6  816.06    37.4  814.16
    47.2  813.43    64.5  804.17    93.3  796.94   111.6  795.58   133.8  790.26
   148.6  788.16   167.1  781.19   188.5  780.13  200.73775.1455   218.9  774.38
  230.78 775.146   241.1   778.1     267  779.16   274.4  780.62   285.5  787.78
   307.7  798.87     341  813.23   363.1   829.9   377.9  845.38   385.3  854.77
   395.3   864.8   403.8  875.62   414.3  886.84   422.3  893.23   432.3   898.4
#Mann= 3 ,-1,0
       0      .1       0  200.73    .045       0  230.78      .1       0
Bank Sta=200.73,230.78
XS Rating Curve= 0 ,0
Exp/Cntr(USF)=0,0
Exp/Cntr=0.3,0.1

Type RM Length L Ch R = 1 ,11735   ,170.7,164.5,155.5
XS GIS Cut Line= 5
1594932.06459717465553.2476690111595012.32296684465597.713787422
1595063.94786359465652.1188623461595132.78105925465724.658087343
1595263.24837297465864.775056773
#Sta/Elev= 30
       0  845.88      10  837.67    21.3  829.68    47.6  813.06    66.3  808.09
    77.6  802.01    97.5  793.65   107.1   790.5   126.1  786.65   145.7  779.75
     162  778.16   178.2  773.35   194.5  772.57  202.18769.8214   226.2  768.58
  241.67769.8206   245.5  770.29   254.8  773.56     271  774.79   326.8  775.68
     350  777.32   366.9  780.23   382.5  778.54   394.1  778.69   398.7  779.96
     408  785.03   420.7  789.06   437.7  792.34   449.8  792.24   458.2  794.59
#Mann= 3 ,-1,0
       0      .1       0  202.18    .045       0  241.67      .1       0
Bank Sta=202.18,241.67
XS Rating Curve= 0 ,0
Exp/Cntr(USF)=0,0
Exp/Cntr=0.3,0.1

Type RM Length L Ch R = 1 ,11570   ,195,192.3,190.1
XS GIS Cut Line= 3
1594804.14618573465751.3359701681595158.60952797465858.402610201
1595238.64963751465912.455671188
#Sta/Elev= 30
       0  899.48    12.6  890.71    36.6  876.91    50.3  866.67      64  858.47
    73.4  852.05      88   843.7    94.8  838.43   110.3  827.86   122.2  818.16
   135.9  805.64   147.1  797.25   160.3   784.2   170.2  771.03   173.6  768.06
  176.27767.0856   183.9  766.32  205.64767.0858   221.6  769.29   245.6   769.3
   297.5  770.87   355.3  775.67   365.6  776.03   372.8  777.43   388.6  784.18
   396.5  786.46   412.3  789.47   441.7  792.87   455.8  796.87   466.9  798.44
#Mann= 5 ,-1,0
       0      .1       0     130     .06       0  176.27    .045       0
  205.64     .06       0     350      .1       0
Bank Sta=176.27,205.64
XS Rating Curve= 0 ,0
Exp/Cntr(USF)=0,0
Exp/Cntr=0.3,0.1

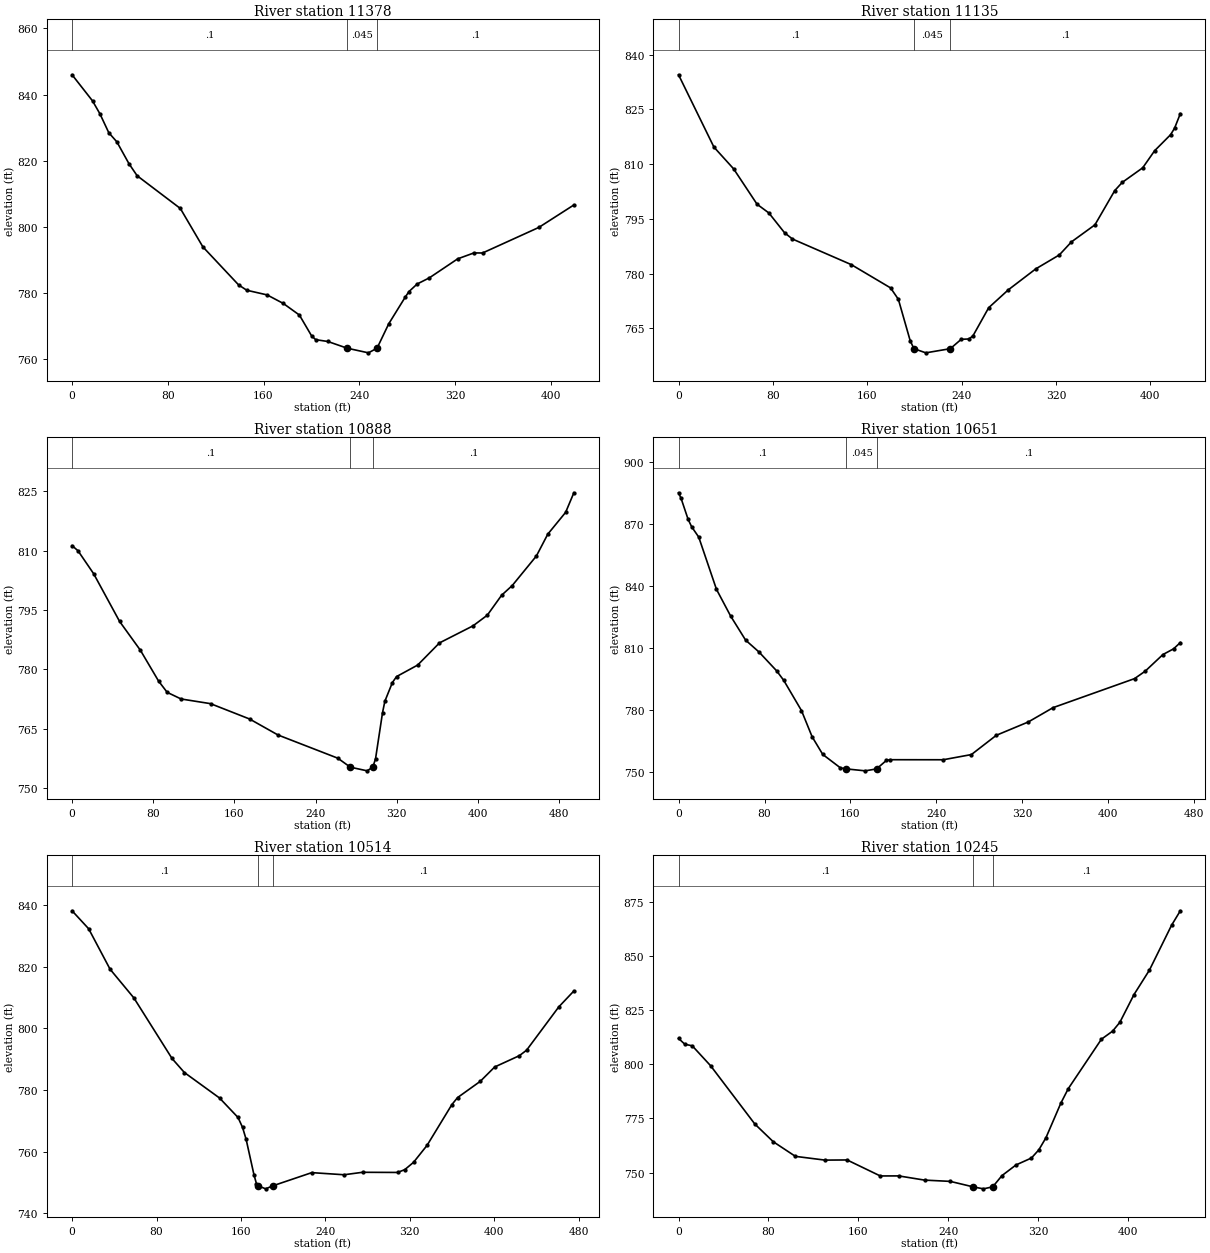
Type RM Length L Ch R = 1 ,11378   ,246.1,243.3,240.9
XS GIS Cut Line= 2
1594789.80067389465923.927546757 1595195.4997286466030.079869508
#Sta/Elev= 30
       0  846.01    17.1  838.12    23.3   834.2    30.7  828.49    37.4  825.76
    47.6  819.11    54.4  815.49    90.5   805.6   109.3  794.01   139.2   782.5
     146  780.89     163  779.48   176.5  776.91     190  773.39   200.2   767.1
   203.6  765.95   213.8   765.4  229.89763.3765   247.7  761.97  254.91763.3783
   264.7  770.76   278.6  778.89   281.6  780.49   288.4  782.77   298.6  784.63
   322.3  790.38   335.9  792.17   343.1  792.15   390.1  799.87   419.4  806.66
#Mann= 3 ,-1,0
       0      .1       0  229.89    .045       0  254.91      .1       0
Bank Sta=229.89,254.91
XS Rating Curve= 0 ,0
Exp/Cntr(USF)=0,0
Exp/Cntr=0.3,0.1

Type RM Length L Ch R = 1 ,11135   ,240.6,246.7,252
XS GIS Cut Line= 6
1594694.71730284466155.8691671791594780.97959751466170.533507928
1594854.91875409466183.1030365821594953.50451492466199.862189427
1595027.44399959466212.4313900021595112.95695193466233.388041005
#Sta/Elev= 30
       0  834.51      30  814.69    46.7  808.73    66.6  799.02    76.6  796.63
    89.9  791.21    96.6  789.49   146.5  782.47   179.8  776.09   186.4  772.97
   196.4  761.66  199.56 759.434   209.7  758.29  230.48 759.432   239.7     762
   246.3  762.09   249.7  762.97     263  770.66   279.6  775.55   302.9   781.3
   322.9  785.13   333.2  788.71   353.1  793.38   369.9  802.77   376.2     805
   393.6  809.01   403.7  813.69   417.2  818.07   420.6  819.85   425.5  823.86
#Mann= 3 ,-1,0
       0      .1       0  199.56    .045       0  230.48      .1       0
Bank Sta=199.56,230.48
XS Rating Curve= 0 ,0
Exp/Cntr(USF)=0,0
Exp/Cntr=0.3,0.1

Type RM Length L Ch R = 1 ,10888   ,248,236.8,227.1
XS GIS Cut Line= 4
1594648.45590846466221.3088500151594772.74408891466370.893500295
1594916.97367817   466482.0827871595027.16305061466523.642482412
#Sta/Elev= 30
       0  811.23     5.8  809.95    21.2  804.16    46.8  792.09    67.4  784.76
    85.2  777.02    93.7  774.16   107.4  772.48   136.4   771.3   174.9  767.42
   202.9  763.38   261.8  757.52   274.2  755.24   290.8  754.32  296.37755.2899
     299  757.37   305.9  769.05   308.2  771.92   315.6  776.63   319.7  778.14
   340.5  781.05     362  786.65   395.1  790.97   409.1  793.65   423.2  798.69
   433.7  801.15   457.5  808.62   468.7  814.13   486.3  819.65   494.4  824.59
#Mann= 3 ,-1,0
       0      .1       0   274.2    .045       0  296.37      .1       0
Bank Sta=274.2,296.37
XS Rating Curve= 0 ,0
Exp/Cntr(USF)=0,0
Exp/Cntr=0.3,0.1

Type RM Length L Ch R = 1 ,10651   ,145.6,137.3,130.6
XS GIS Cut Line= 2
1594525.15863102466621.7955991841594989.80705912466576.058393733
#Sta/Elev= 30
       0  885.18     2.4  882.43     8.9  872.32    12.2  868.72    18.8  863.71
    35.3  838.41    48.5  825.46    62.4  813.82    74.8   808.1    91.3  798.93
    97.9  794.32   114.4  779.69   124.3  767.01   134.2  758.45   150.7  751.92
  156.26751.4404   173.7  750.51  184.23751.4406   193.5   755.6   196.8   755.9
   246.3  755.88   272.5  758.39   295.7  767.73   325.4  774.17   348.5  781.12
   424.3  795.17   434.2  798.77   450.7  806.83   460.6  809.59   466.9  812.63
#Mann= 3 ,-1,0
       0      .1       0  156.26    .045       0  184.23      .1       0
Bank Sta=156.26,184.23
XS Rating Curve= 0 ,0
Exp/Cntr(USF)=0,0
Exp/Cntr=0.3,0.1

Type RM Length L Ch R = 1 ,10514   ,262.8,268.8,277.5
XS GIS Cut Line= 4
1594624.94889745466860.8764458591594716.40205646466764.245718564
1594824.52064748466641.4584727871594997.30277881466595.708798295
#Sta/Elev= 30
       0   838.2    15.7  832.37      36  819.24    58.6   809.9    94.7  790.26
   106.4  785.71   139.7  777.44   157.2  771.13   161.5  767.91   164.9  764.03
   172.4  752.43   174.7  749.62  176.27748.9593   183.4  747.96  190.19748.9434
   227.1  753.22   257.7  752.53   275.2  753.33   308.4  753.28   315.2  754.19
   323.5  756.56   336.3  762.06   359.8  775.28   365.2  777.57   386.7  782.84
   400.4  787.51   423.8  791.18   430.6  792.95   461.1     807   475.4  812.17
#Mann= 3 ,-1,0
       0      .1       0  176.27    .045       0  190.19      .1       0
Bank Sta=176.27,190.19
XS Rating Curve= 0 ,0
Exp/Cntr(USF)=0,0
Exp/Cntr=0.3,0.1

Type RM Length L Ch R = 1 ,10245   ,108.6,109.4,111.7
XS GIS Cut Line= 2
 1594672.7962092466887.5277162151595119.23782069466882.972189567
#Sta/Elev= 30
       0  811.94     5.6  809.24    12.2  808.52    28.6  799.28    67.9  772.41
    84.3  764.24     104  757.49   130.3  755.76     150  755.83   179.5  748.45
   195.9  748.47   218.9  746.53   241.8  745.94   262.4  743.38   271.3   742.5
  279.56743.4222   287.8  748.61   300.3  753.53     314  756.72   320.6   760.5
   326.9  766.05   340.2  782.06   346.8  788.75   376.3  811.57   386.2  815.27
   392.7  819.36   405.3  832.19     419  843.45   438.7  864.15   446.5  870.84
#Mann= 3 ,-1,0
       0      .1       0   262.4    .045       0  279.56      .1       0
Bank Sta=262.4,279.56
XS Rating Curve= 0 ,0
Exp/Cntr(USF)=0,0
Exp/Cntr=0.3,0.1

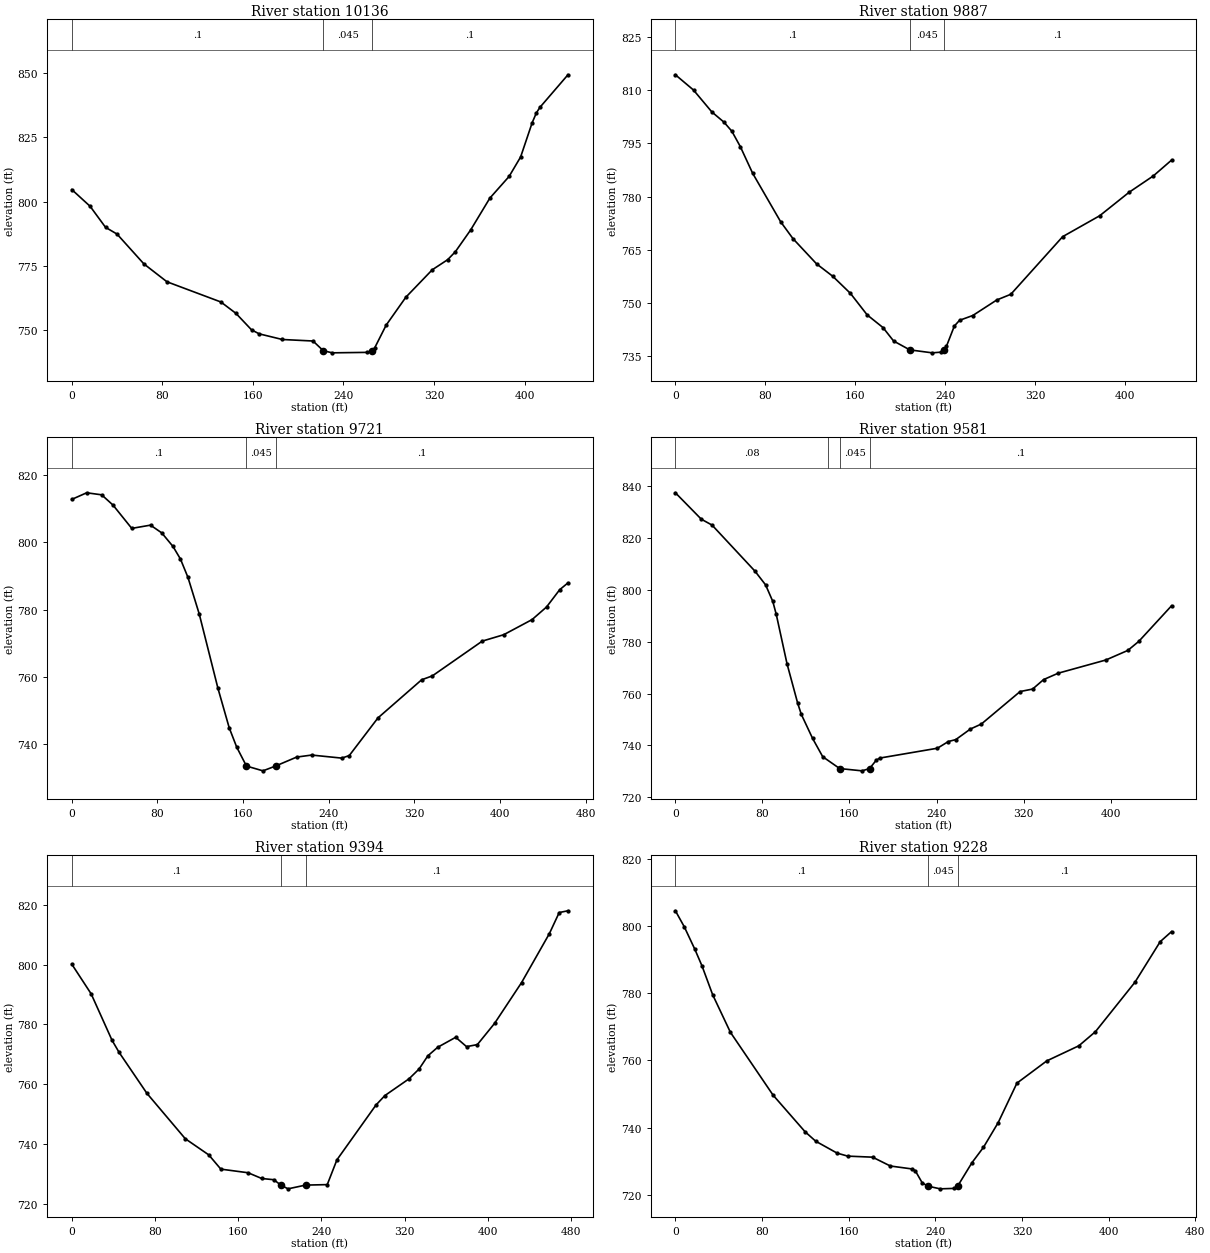
Type RM Length L Ch R = 1 ,10136   ,240.6,248.4,264.7
XS GIS Cut Line= 2
1594675.85087076466925.5372472551595099.31268523467038.467483074
#Sta/Elev= 30
       0   804.7    16.2  798.19    29.8  790.02      40  787.38    63.7  775.79
    84.1  768.83   131.7  760.98     145  756.56   158.8  750.14   165.6  748.58
     186  746.39   213.1   745.8  222.11742.0477   230.1   741.2   260.7  741.38
  265.16742.0481   267.5  743.06   277.7  751.97   295.1  762.83   318.4  773.49
     332  777.42   338.8   780.5   352.4  789.03   369.3  801.37   386.3   809.8
   396.5  817.39   406.7  830.71   410.4  834.51   413.5  836.66   438.3  849.35
#Mann= 3 ,-1,0
       0      .1       0  222.11    .045       0  265.16      .1       0
Bank Sta=222.11,265.16
XS Rating Curve= 0 ,0
Exp/Cntr(USF)=0,0
Exp/Cntr=0.3,0.1

Type RM Length L Ch R = 1 ,9887    ,175.4,166.1,159.9
XS GIS Cut Line= 6
1594609.67973351467020.2230637611594688.09821185467078.256084183
1594729.60665902467141.2228217661594788.92543802467221.814852187
1594835.59397985467280.5266770061594915.08430643467328.920281017
#Sta/Elev= 30
       0   814.4    16.1  810.09    32.4  803.91    43.2  801.02    50.2  798.46
    57.7  794.13    68.7  786.58    93.6  772.89   104.5  768.15   125.5  761.02
   139.9  757.51   155.6  752.69   170.5  746.61   184.6  743.02     194  739.24
  208.36736.7383   228.3   735.9   236.4   736.1  238.84736.7385   240.9  737.69
     248  743.47   252.6  745.08   264.4  746.44   285.7  750.82   298.2  752.43
   344.3   768.7   377.2   774.6   403.4  781.24   424.9  785.85   441.1  790.31
#Mann= 3 ,-1,0
       0      .1       0  208.36    .045       0  238.84      .1       0
Bank Sta=208.36,238.84
XS Rating Curve= 0 ,0
Exp/Cntr(USF)=0,0
Exp/Cntr=0.3,0.1

Type RM Length L Ch R = 1 ,9721    ,146.5,140,136
XS GIS Cut Line= 3
1594458.63178672467209.1028964511594720.58123612467306.814199006
1594901.45109404 467339.03813921
#Sta/Elev= 30
       0  812.83    13.9   814.8    27.9  814.19    38.5  811.13      56  804.19
    73.5  805.16      84  802.85    94.5  798.81   101.5  795.04   108.5  789.57
     119   778.7   136.5  756.52     147  744.78     154  739.02  163.09733.3881
   178.5  731.96  190.27733.3896     210  736.06     224  736.66   252.1  735.75
   259.1  736.51   285.9  747.73   326.7  759.09   336.7  760.25   383.3  770.61
   403.3  772.51   429.8  777.02   443.3  780.77   455.6  785.93   463.3  787.95
#Mann= 3 ,-1,0
       0      .1       0  163.09    .045       0  190.27      .1       0
Bank Sta=163.09,190.27
XS Rating Curve= 0 ,0
Exp/Cntr(USF)=0,0
Exp/Cntr=0.3,0.1

Type RM Length L Ch R = 1 ,9581    ,202.9,186.8,171.5
XS GIS Cut Line= 3
1594457.74704044467416.2166094771594683.49039826467408.032560251
1594907.86974789467356.882252587
#Sta/Elev= 30
       0  837.32    23.8  827.15    33.7  824.87    73.1  807.15    82.9  801.84
    89.5  795.49    92.7  790.49   102.6  771.44   112.4  756.25   115.7  751.99
   126.1   742.7   135.4  735.66     151   731.1   171.5  730.22  178.44   731.1
   184.7  734.37     188  735.15   240.8  738.93   250.9  741.52   257.7  742.25
   271.1  746.32   281.2  748.25   316.8  760.76   328.3  761.72   338.4  765.37
   351.9  767.84   395.6  772.91   415.8   776.6   425.9  780.09     456   793.8
#Mann= 4 ,-1,0
       0     .08       0     140      .1       0     151    .045       0
  178.44      .1       0
Bank Sta=151,178.44
XS Rating Curve= 0 ,0
Exp/Cntr(USF)=0,0
Exp/Cntr=0.3,0.1

Type RM Length L Ch R = 1 ,9394    ,147.6,166,179.2
XS GIS Cut Line= 4
1594571.64172551 467625.591868851594719.63661568467594.219680149
1594749.64479618467496.0110894341594961.06606786467425.082662806
#Sta/Elev= 30
       0  800.16    18.6  790.25    38.7  774.71    45.4  770.71    72.2  756.98
   109.1  741.79   131.7  736.38   143.3  731.62   169.5  730.41   182.6  728.49
   194.2  728.08     201  726.28   207.9  725.03   224.7  726.28   245.6  726.44
   254.9  734.73   292.4  753.04     301  756.22   324.2  761.82   333.9  765.11
   342.3  769.51   351.8  772.38   369.1  775.71   379.5  772.59   389.9  773.26
   406.5  780.38   432.4     794   459.1  810.35   468.6  817.43     477  818.02
#Mann= 3 ,-1,0
       0      .1       0     201    .045       0   224.7      .1       0
Bank Sta=201,224.7
XS Rating Curve= 0 ,0
Exp/Cntr(USF)=0,0
Exp/Cntr=0.3,0.1

Type RM Length L Ch R = 1 ,9228    ,222.4,213.2,209.4
XS GIS Cut Line= 3
1594575.05174602 467647.41600012 1594851.2634074467644.687983711
1595023.81044526467586.717635025
#Sta/Elev= 30
       0  804.51     8.2  799.75      18  793.03    24.6  788.09    34.4  779.55
    50.8  768.37    90.2  749.68   119.7  738.81   129.6  735.97   149.3  732.44
   159.1  731.54   182.1  731.23   198.5   728.6   218.2  727.74   221.5  727.21
     228  723.56  233.33722.6008   244.5  721.81   257.5  721.94  260.62722.6004
   273.9   729.6   284.5  734.16   298.1  741.51   315.4  753.25     343  759.87
   372.6  764.36   387.9  768.55   424.4  783.26   447.7  795.32   458.2  798.32
#Mann= 3 ,-1,0
       0      .1       0  233.33    .045       0  260.62      .1       0
Bank Sta=233.33,260.62
XS Rating Curve= 0 ,0
Exp/Cntr(USF)=0,0
Exp/Cntr=0.3,0.1