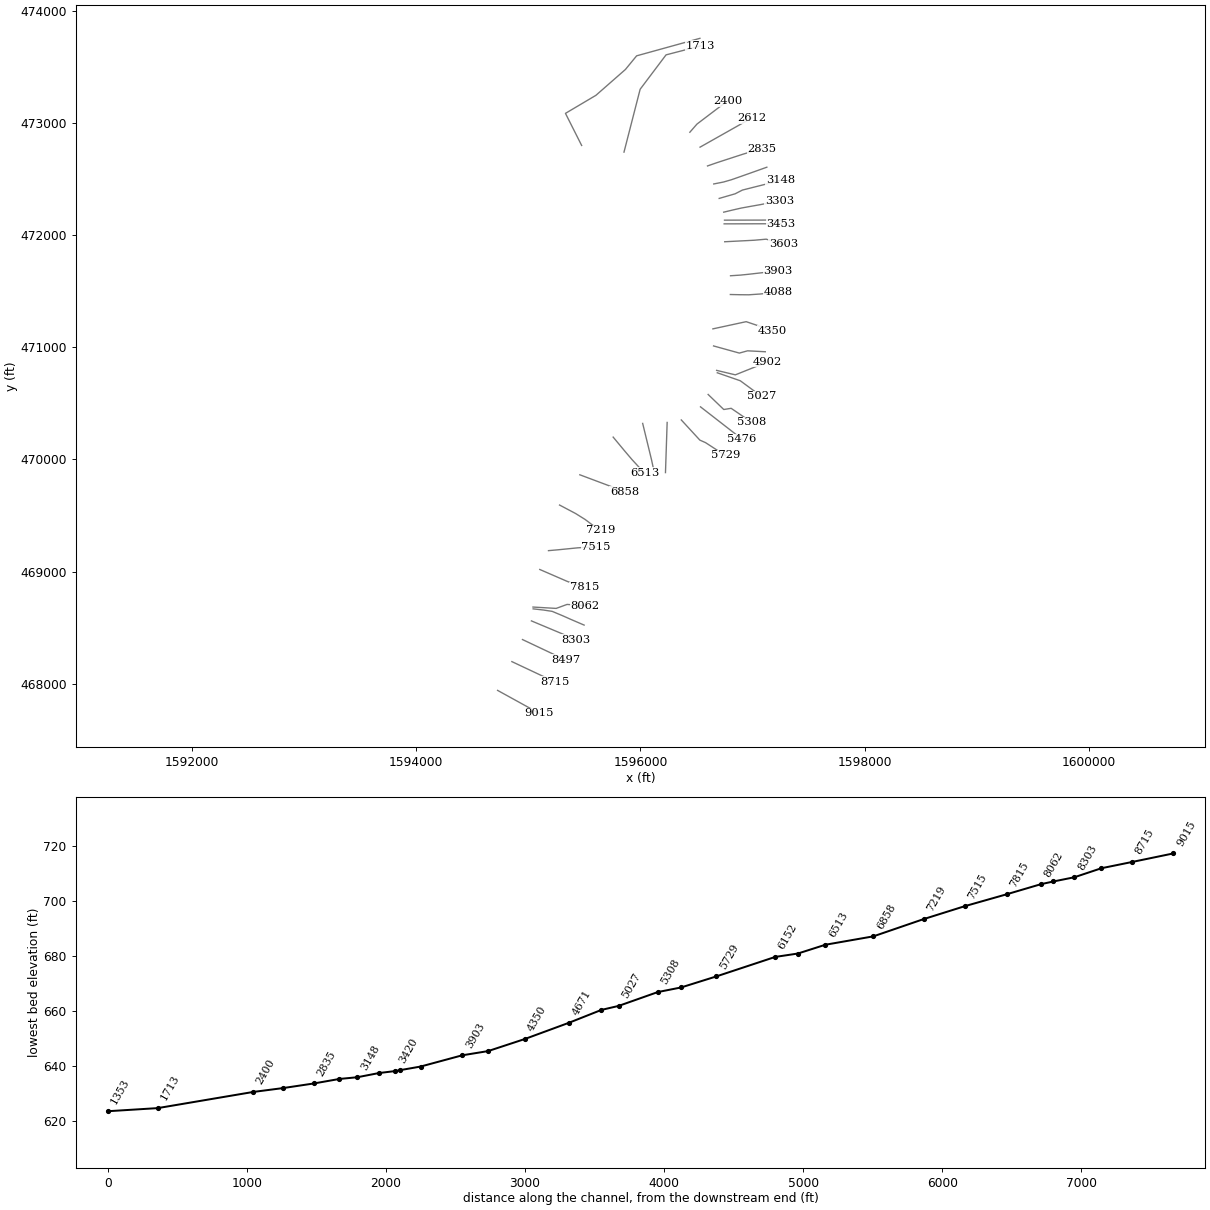
HEC-RAS study CoonRn.prj: CoonRn

--- CoonRn.g01 (geometry) --- (continued)

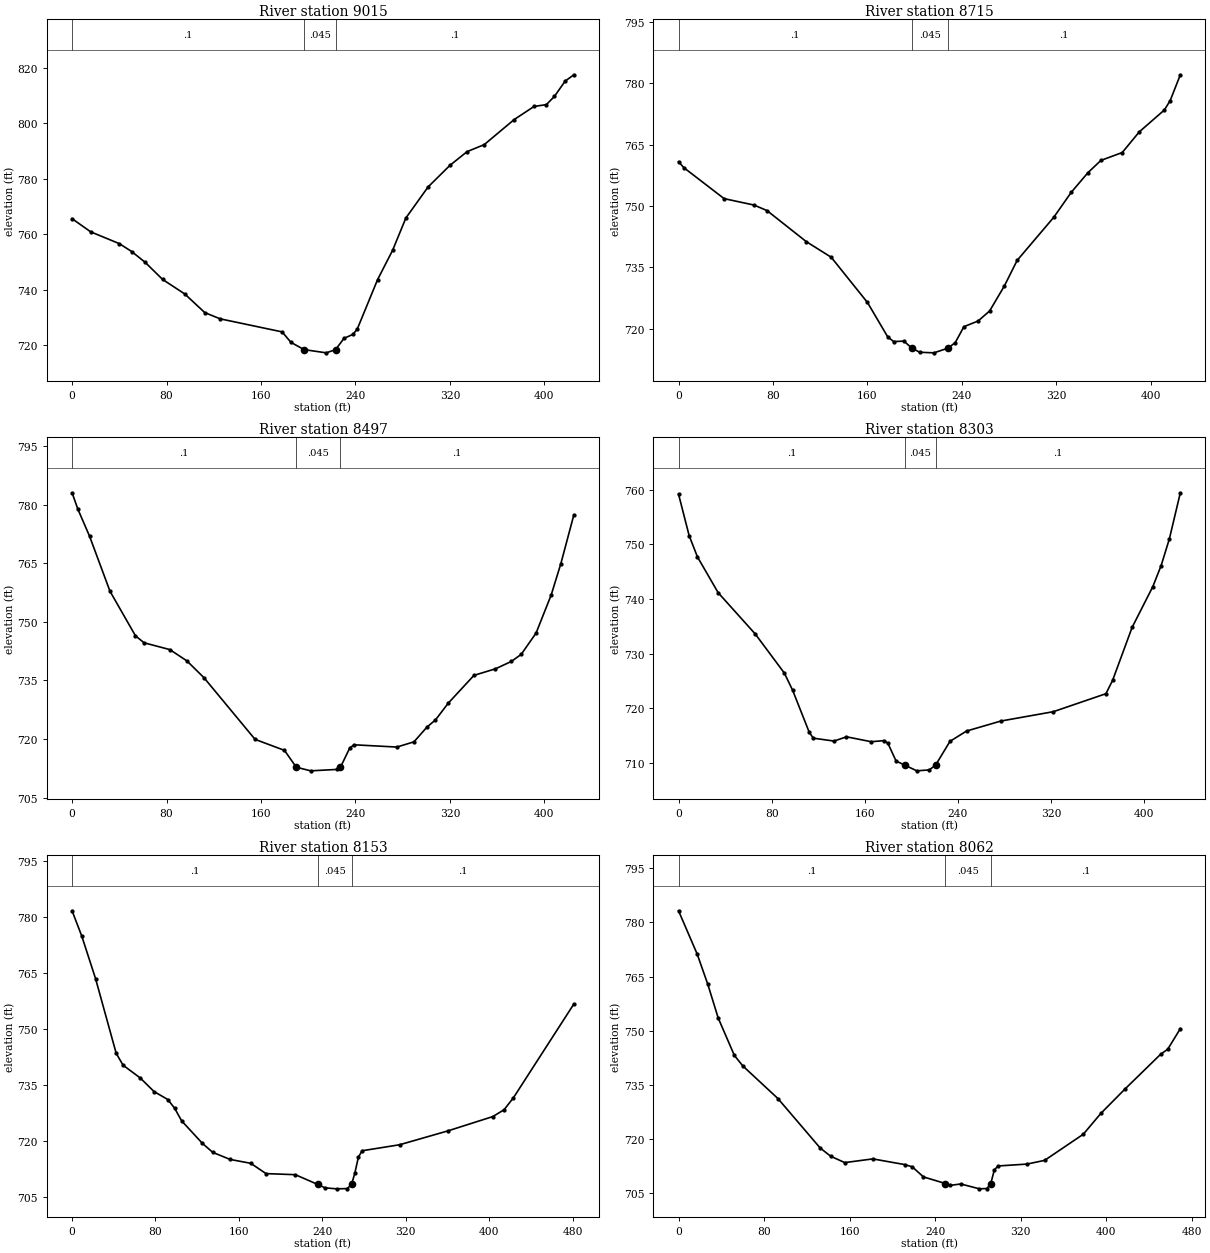
Type RM Length L Ch R = 1 ,9015    ,299,300,300.8
XS GIS Cut Line= 6
1594725.99020617467940.5279994161594802.63834684467898.322703257
1594868.33703434467862.1469225881594955.93528435467813.912767082
1595021.63397184467777.7366583351595098.28244059467735.531690255
#Sta/Elev= 30
       0  765.59    15.8  760.84      40   756.6    50.5  753.75    61.8   749.9
    76.7  743.69    95.5  738.44   112.4  731.74   125.4   729.5   177.9  724.79
   185.4  721.01  196.49718.4035   215.3  717.24  223.22 718.402   230.3  722.47
   237.8  723.87   241.5  725.75   258.8  743.67   271.5   754.2   282.7  765.82
   301.5  777.01   320.1  784.83   334.6  789.76   349.1  792.28   374.5  801.33
   391.3  806.04   401.7  806.69   408.5  809.63   417.6  815.16     425  817.45
#Mann= 3 ,-1,0
       0      .1       0  196.49    .045       0  223.22      .1       0
Bank Sta=196.49,223.22
XS Rating Curve= 0 ,0
Exp/Cntr(USF)=0,0
Exp/Cntr=0.3,0.1

Type RM Length L Ch R = 1 ,8715    ,218.1,217.9,217.9
XS GIS Cut Line= 6
1594853.40760225468196.9963185041594932.57935992468159.739175171
1595000.44077276468127.8041996661595090.92254718468085.224560425
   1595158.78396468053.2899129991595237.95571767468016.032769665
#Sta/Elev= 30
       0  760.85     4.6  759.38    38.6  751.83      64  750.25    74.9  748.91
   108.2  741.31   129.3  737.49     160  726.43   177.2  717.99   182.2  716.86
   190.9  716.97  197.55715.2625   204.3  714.24   216.3   714.1  228.39715.2621
   234.4  716.62   241.7   720.5   253.7  721.88   263.5  724.35   275.9  730.43
   286.8  736.72   317.8  747.26   332.6  753.37   346.8  758.19   357.7  761.17
   375.8  763.11   390.3  768.18   411.5  773.52   416.4  775.81     425  782.13
#Mann= 3 ,-1,0
       0      .1       0  197.55    .045       0  228.39      .1       0
Bank Sta=197.55,228.39
XS Rating Curve= 0 ,0
Exp/Cntr(USF)=0,0
Exp/Cntr=0.3,0.1

Type RM Length L Ch R = 1 ,8497    ,193.2,194,194.5
XS GIS Cut Line= 6
1594948.04013859 468393.755109591595027.14431109468356.354265761
1595094.94765316468324.2965870911595185.35232801468281.552906182
1595253.15567008468249.495227512 1595332.2595145468212.094711762
#Sta/Elev= 30
       0  783.07     4.9  778.88    14.8  771.96    32.1  757.86    53.7  746.44
      61  744.65    82.8  742.91    97.3  740.01   111.8  735.68     155  719.92
   179.9   717.1  189.89 712.791   202.1  711.86   224.3  712.22  227.33712.7917
   235.2  717.72   238.8  718.53   275.1  717.95   289.6  719.29   300.6  723.07
   307.8   724.9   318.7  729.22   340.4  736.31   358.6  737.99   372.1  739.88
   380.4  741.69     393  747.14   405.8   756.9     414  764.94     425  777.42
#Mann= 3 ,-1,0
       0      .1       0  189.89    .045       0  227.33      .1       0
Bank Sta=189.89,227.33
XS Rating Curve= 0 ,0
Exp/Cntr(USF)=0,0
Exp/Cntr=0.3,0.1

Type RM Length L Ch R = 1 ,8303    ,150.2,150.4,150.7
XS GIS Cut Line= 2
1595027.59940371468560.1028163741595425.20124655468393.577809255
#Sta/Elev= 30
       0  759.16     9.1  751.59    16.2  747.71      34  741.16      66  733.58
    90.9  726.46      98  723.33   112.3  715.63   115.8  714.56   133.6  714.03
   144.3  714.81   165.6  713.91   176.3  714.11   179.8  713.66   186.9  710.38
   194.2  709.65   204.7  708.59   215.4  708.76   220.9  709.65   233.2  713.98
   247.4  715.86   276.9  717.69     322   719.4   367.2  722.69   372.9  725.12
   389.7  734.82   407.5  742.27   414.6   746.1   421.7  750.99   431.1  759.41
#Mann= 3 ,-1,0
       0      .1       0   194.2    .045       0   220.9      .1       0
Bank Sta=194.2,220.9
XS Rating Curve= 0 ,0
Exp/Cntr(USF)=0,0
Exp/Cntr=0.3,0.1

Type RM Length L Ch R = 1 ,8153    ,68.2,90.4,98.9
XS GIS Cut Line= 6
1595043.19982736 468667.423604711595135.65403878468656.968573137
1595212.98131195468645.0847386411595305.24425078468606.455550803
1595373.78020295468575.9953098881595497.70911868468522.683494343
#Sta/Elev= 30
       0  781.74     9.3  774.94    22.5  763.54    42.3  743.47    48.9  740.27
    65.4  736.83    78.6  733.19    91.8  731.05    98.4  728.68   105.1  725.31
     125  719.27   134.9  716.86   151.5  714.96   171.3  713.92     186  711.15
   214.1  710.86   235.5708.2529   242.6  707.33   253.7  707.06   263.9  707.13
  268.03708.2516   271.1  711.22   274.6   715.6   278.2  717.29   314.1   718.9
   360.7  722.65   403.6  726.48   414.3  728.31   423.2   731.5   481.2   756.7
#Mann= 3 ,-1,0
       0      .1       0   235.5    .045       0  268.03      .1       0
Bank Sta=235.5,268.03
XS Rating Curve= 0 ,0
Exp/Cntr(USF)=0,0
Exp/Cntr=0.3,0.1

Type RM Length L Ch R = 1 ,8062    ,262.2,247.3,233.5
XS GIS Cut Line= 4
1595041.63240993468683.5932710921595248.38536821 468671.43133237
1595345.68087799468706.9816147881595503.78608137468695.755209814
#Sta/Elev= 30
       0  783.24    17.4  771.25    27.4  762.81    37.1  753.47    52.2   743.1
    60.1  740.18    92.9  731.14   132.4  717.42   142.2  715.13   155.4  713.35
   181.7  714.38   211.5   712.8   218.5  712.19     229  709.38  249.58707.5425
   253.4  707.01   263.9  707.42   281.4  706.07   288.4  706.16  291.96707.5479
   295.3  711.33   298.8  712.42   325.8  712.94   342.3  713.97   378.5  721.23
   394.9  727.01   417.9   733.9   450.8  743.42   457.4  744.81   469.2  750.53
#Mann= 3 ,-1,0
       0      .1       0  249.58    .045       0  291.96      .1       0
Bank Sta=249.58,291.96
XS Rating Curve= 0 ,0
Exp/Cntr(USF)=0,0
Exp/Cntr=0.3,0.1

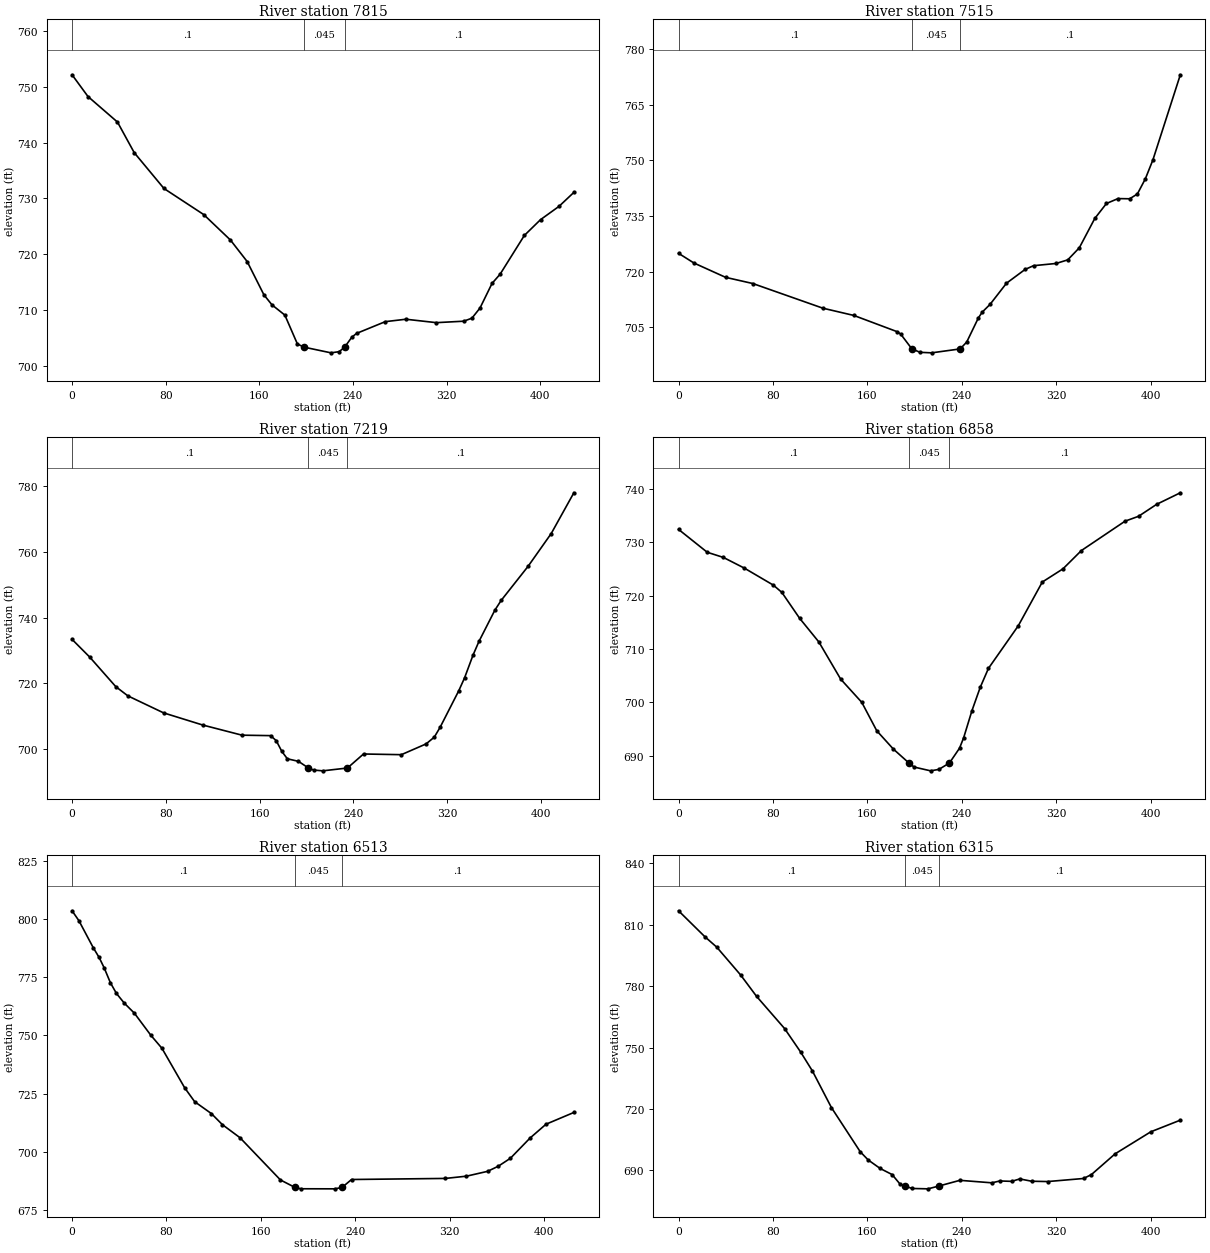
Type RM Length L Ch R = 1 ,7815    ,291.7,300,311.9
XS GIS Cut Line= 6
1595102.14594993469018.5914600941595182.41350593468983.758196428
1595251.21422134468953.9009726791595342.94861792468914.091341004
1595412.74867517468886.5362780091595499.42829184 468858.32275176
#Sta/Elev= 30
       0  752.13    13.6  748.24    38.8  743.67    53.1   738.2    78.5  731.79
   112.5  727.12   135.3  722.57   149.6  718.72   163.9  712.77   170.8  710.97
   181.8  709.14   192.5  703.98  198.11703.4104   221.2  702.39   228.2   702.6
  232.89703.4094     239  705.19   243.1  705.87   267.6  707.97   285.2   708.4
   311.2  707.79   334.6  708.05   341.6  708.59   348.5   710.4   358.8  714.81
   365.7  716.46   386.4  723.39   400.2  726.21     416  728.59   428.7  731.09
#Mann= 3 ,-1,0
       0      .1       0  198.11    .045       0  232.89      .1       0
Bank Sta=198.11,232.89
XS Rating Curve= 0 ,0
Exp/Cntr(USF)=0,0
Exp/Cntr=0.3,0.1

Type RM Length L Ch R = 1 ,7515    ,304.7,296.4,279.9
XS GIS Cut Line= 6
1595180.00274959469186.4474235921595267.16071175469194.231856838
  1595341.795405469201.624558583  1595441.299143469211.574998006
1595516.19006935469216.2144244161595603.87755801469217.029383421
#Sta/Elev= 30
       0  724.91      13   722.3    39.9  718.43    62.9  716.77   122.3  710.12
   148.6  708.16   184.9  703.83   188.2  703.16  197.75699.1473   204.7  698.23
   214.5  698.09  238.62699.1486   244.2     701   254.1  707.52   257.4  709.08
     264  711.16   277.9  716.85   293.6  720.55   300.8  721.57   319.9  722.17
   329.8  723.14   339.6  726.39   352.7  734.29   362.6  738.33   372.4  739.65
   382.3   739.6   388.8  740.89   395.6     745     402  750.11   425.2  773.01
#Mann= 3 ,-1,0
       0      .1       0  197.75    .045       0  238.62      .1       0
Bank Sta=197.75,238.62
XS Rating Curve= 0 ,0
Exp/Cntr(USF)=0,0
Exp/Cntr=0.3,0.1

Type RM Length L Ch R = 1 ,7219    ,357.3,360.7,364
XS GIS Cut Line= 6
1595278.61114818469593.1956258421595355.94268642469552.255747095
1595422.22667459469517.1642818451595507.25143893469464.040044263
1595567.88484783469418.2743877621595641.47886075469367.294830918
#Sta/Elev= 30
       0  733.42      15  728.05    37.3  719.03    47.6  716.22    78.1  711.04
   111.5  707.34     145  704.25   169.4  704.11   174.2  702.59     179  699.31
   183.7  697.06   193.2  696.28  201.71694.2509   206.1  693.63   213.9  693.39
     235694.2524   248.7  698.52     281  698.31   302.1  701.59   309.1  703.65
   314.1  706.67     330  717.79   334.9  721.67   342.2  728.66   347.2  732.79
   360.8  742.32   366.2   745.3   389.1  755.65   408.9  765.66   428.2  778.06
#Mann= 3 ,-1,0
       0      .1       0  201.71    .045       0     235      .1       0
Bank Sta=201.71,235
XS Rating Curve= 0 ,0
Exp/Cntr(USF)=0,0
Exp/Cntr=0.3,0.1

Type RM Length L Ch R = 1 ,6858    ,352.8,345.2,334.7
XS GIS Cut Line= 6
1595459.46544127469862.8106918631595541.39408318469832.087000027
1595611.61868026469805.7527351081595705.25169509469770.640272528
1595775.47629217469744.3060076091595857.40493409469713.582643852
#Sta/Elev= 30
       0   732.4    24.3  728.11      38  727.14    55.8  725.13    80.3  721.95
    87.5  720.59   102.5  715.75   118.9  711.28   137.3  704.34   155.2  699.98
   167.9  694.65   181.9  691.23  195.14688.6102   199.5  687.85   213.5  687.14
   220.5  687.41  229.46688.6108     238  691.39   241.5  693.35   248.5  698.41
   255.5  702.78   262.5  706.35   287.7  714.31   308.1  722.53   325.6     725
   341.2  728.43   378.2  733.94   389.6  734.85   404.9  737.09     425  739.26
#Mann= 3 ,-1,0
       0      .1       0  195.14    .045       0  229.46      .1       0
Bank Sta=195.14,229.46
XS Rating Curve= 0 ,0
Exp/Cntr(USF)=0,0
Exp/Cntr=0.3,0.1

Type RM Length L Ch R = 1 ,6513    ,206.5,197.7,189.8
XS GIS Cut Line= 6
1595756.71269734  470198.7499079 1595812.6269556 470131.44590864
1595860.55336893470073.7567195641595925.39936784469997.622029309
1595976.36350477469942.4561291531596036.36272859469878.545823891
#Sta/Elev= 30
       0   803.5     5.8  799.24    17.9  787.69    22.9  783.48    27.2  779.01
    32.5  772.58    37.6  768.01    44.2  763.87    52.8  759.53    66.8  750.02
    76.2  744.43    95.4  727.51   103.9  721.52   118.1   716.4   127.4  711.66
   142.3  706.06   176.6  687.91  188.87684.7144   193.8  684.12   222.9  684.09
  228.84684.7158   236.9   688.1   316.4  688.56   334.3  689.53   352.2  691.61
   361.2  693.79   371.5  697.21   388.2  705.92   401.7  711.84   425.3  716.89
#Mann= 3 ,-1,0
       0      .1       0  188.87    .045       0  228.84      .1       0
Bank Sta=188.87,228.84
XS Rating Curve= 0 ,0
Exp/Cntr(USF)=0,0
Exp/Cntr=0.3,0.1

Type RM Length L Ch R = 1 ,6315    ,168.2,162.9,160.4
XS GIS Cut Line= 6
1596019.92364192470320.8683830951596040.60470292470235.847555757
1596058.33137351470162.9727015051596081.96715301470065.805901095
1596099.69349551 469992.930718751596118.04188401469907.342635334
#Sta/Elev= 30
       0  816.86    22.3  804.18    32.4  799.06    52.6  785.46    66.1  775.01
    89.8  759.29   103.3   747.9   113.4  738.52   129.5  720.63   153.9  699.03
   160.7  694.99   170.8  690.85   180.9  687.88   187.7  683.15  191.45682.3383
   197.8  681.08   211.3   680.9  220.93682.3378   238.3  685.06   265.4  683.84
   272.1  684.75   282.2  684.56     289  685.75   299.1  684.62   312.6  684.46
     343  685.96   349.7  687.87   369.8  698.03     400  708.79     425  714.49
#Mann= 3 ,-1,0
       0      .1       0  191.45    .045       0  220.93      .1       0
Bank Sta=191.45,220.93
XS Rating Curve= 0 ,0
Exp/Cntr(USF)=0,0
Exp/Cntr=0.3,0.1

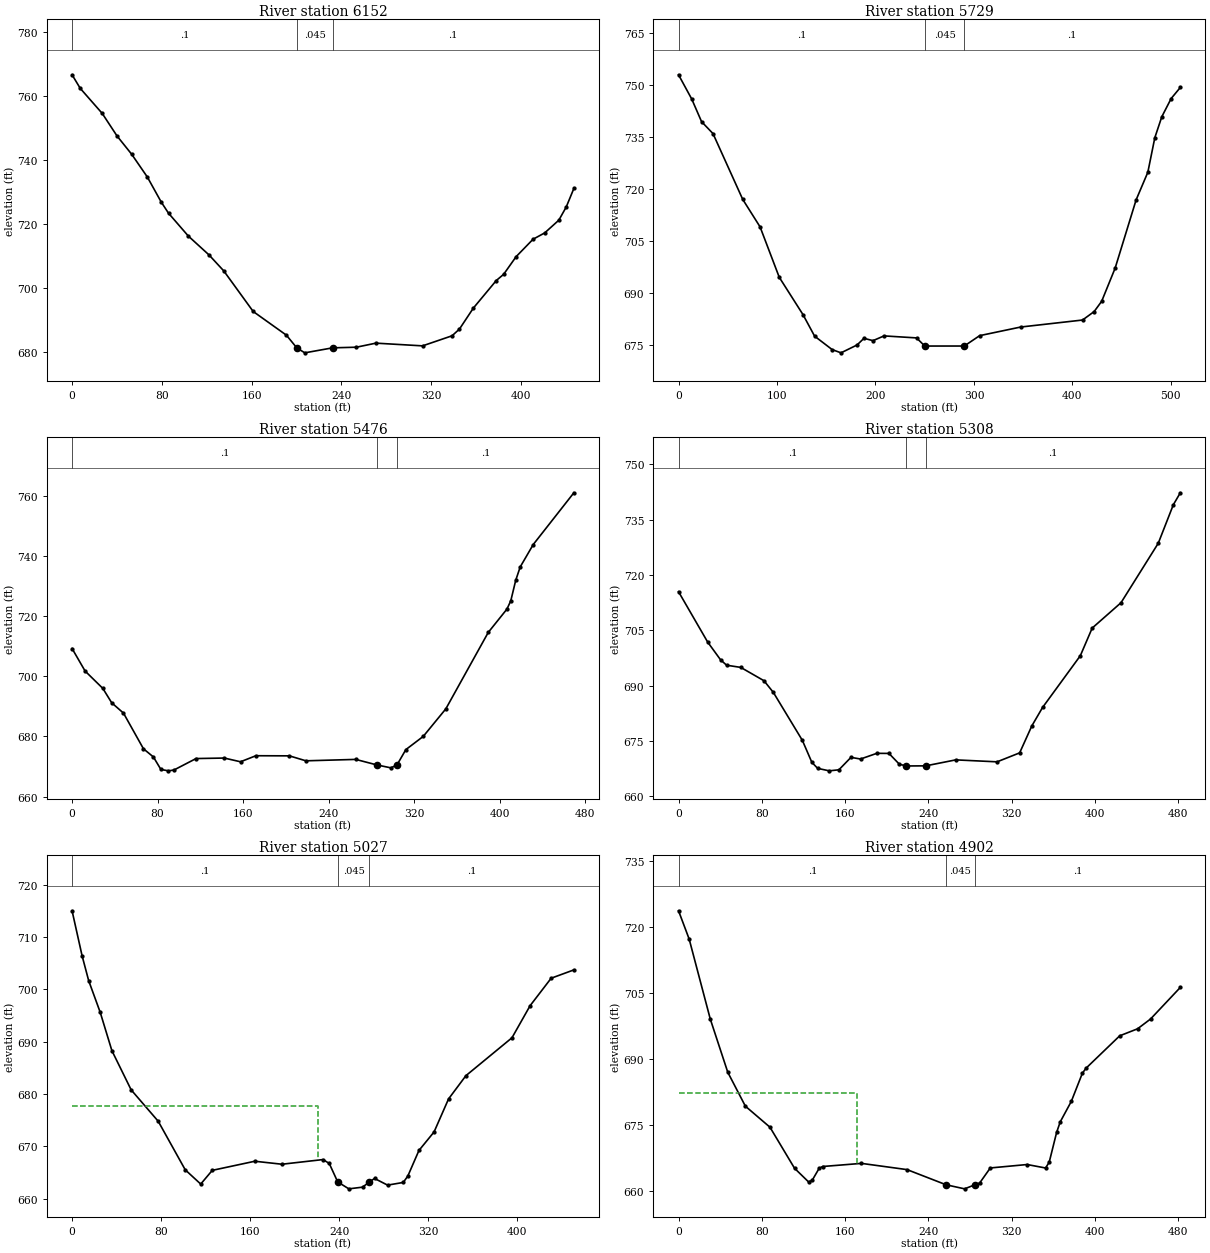
Type RM Length L Ch R = 1 ,6152    ,388.3,423,435.7
XS GIS Cut Line= 2
1596238.22983493470329.4610966511596223.26129496469882.275965177
#Sta/Elev= 30
       0  766.57     7.3  762.32    26.9  754.49    40.1  747.44    53.2  741.71
    67.1  734.62    79.5  726.79      86  723.31   103.7  716.15   122.1  710.27
   135.3  705.26   161.5  692.59   191.1  685.19  200.36681.2292   207.5  679.67
  232.26681.2307   253.5  681.43   270.9   682.7   312.5  681.85   338.8     685
   345.4   687.1   357.8  693.66   378.2  702.26   384.8  704.21   395.9  709.72
     411  715.17   421.4  717.15     434  721.13   440.6  725.25   447.4  731.04
#Mann= 3 ,-1,0
       0      .1       0  200.36    .045       0  232.26      .1       0
Bank Sta=200.36,232.26
XS Rating Curve= 0 ,0
Exp/Cntr(USF)=0,0
Exp/Cntr=0.3,0.1

Type RM Length L Ch R = 1 ,5729    ,269.9,253.6,250.4
XS GIS Cut Line= 4
1596364.44290519470351.7210440141596530.13781546470171.701949416
1596580.18247544470149.7126291181596756.56572285470035.170987583
#Sta/Elev= 30
       0  752.86    13.4  745.86    23.4  739.32      35  735.88    65.2  716.89
    82.8  708.96   102.3   694.4   126.4  683.63   138.2  677.41     156  673.54
     165   672.6   181.3  674.87   188.3  676.79   197.5  676.12   208.7  677.49
   241.7  676.91  250.09 674.561  290.19674.5678   305.8  677.56   347.5  680.05
   410.3  682.07   422.1  684.52   429.7  687.47   443.4  697.05   464.7  716.75
   476.6  724.72   483.7   734.7   490.8  740.75   500.3  746.01   509.6   749.2
#Mann= 3 ,-1,0
       0      .1       0  250.09    .045       0  290.19      .1       0
Bank Sta=250.09,290.19
XS Rating Curve= 0 ,0
Exp/Cntr(USF)=0,0
Exp/Cntr=0.3,0.1

Type RM Length L Ch R = 1 ,5476    ,160.6,167.4,176.1
XS GIS Cut Line= 2
1596535.55104381470468.6449387331596906.28534413470180.612905403
#Sta/Elev= 30
       0  709.23    12.2  701.74    28.8  695.97    37.1  691.19    48.1  687.77
    66.8  675.91    76.1   673.2    83.1  669.05    90.2  668.59    95.3  668.86
     116  672.67   142.4  672.84   157.6   671.6     172  673.61   203.3  673.57
   218.8  671.92   265.4  672.39   284.9  670.58   298.3  669.58  304.07670.5889
   312.3  675.64   328.6  680.04   349.7  689.18   389.4  714.58   406.9  722.33
   410.5   725.1   415.1  731.89   419.3  736.33   431.5  743.78   469.5  760.97
#Mann= 3 ,-1,0
       0      .1       0   284.9    .045       0  304.07      .1       0
Bank Sta=284.9,304.07
XS Rating Curve= 0 ,0
Exp/Cntr(USF)=0,0
Exp/Cntr=0.3,0.1

Type RM Length L Ch R = 1 ,5308    ,289.3,281.2,274.3
XS GIS Cut Line= 4
 1596603.7564789470578.9424483421596743.18842868470444.814974912
1596809.11549189470455.4239276121596992.49881715470330.389842211
#Sta/Elev= 30
       0  715.44      28   701.8    40.4  696.99    46.2  695.53    59.8  694.94
    82.1  691.33    91.1  688.17     119  675.17   128.1  669.23   133.7  667.59
   144.8  666.92   154.1   667.2   165.7  670.57   174.9  670.12   190.5  671.66
   202.2  671.64   212.2  668.71   218.9  668.24  237.59668.2723   266.4  669.89
   306.1  669.36   327.8  671.79   339.5  679.09   349.8  684.08   386.1   698.1
   397.5  705.59   425.2  712.46     461  728.57   475.5  739.01   482.2  742.24
#Mann= 3 ,-1,0
       0      .1       0   218.9    .045       0  237.59      .1       0
Bank Sta=218.9,237.59
XS Rating Curve= 0 ,0
Exp/Cntr(USF)=0,0
Exp/Cntr=0.3,0.1

Type RM Length L Ch R = 1 ,5027    ,109.7,124.9,138.1
XS GIS Cut Line= 3
1596685.27066509470772.3618847681596890.60043143470701.066827013
 1597078.8193839470562.754414969
#Sta/Elev= 30
       0     715       9  706.41    14.9  701.67    25.3   695.6    35.8  688.28
    53.1   680.8    77.4  674.81   101.7  665.53   115.6  662.81     126  665.43
   164.2  667.17   188.6   666.6   225.5  667.49   231.1  666.75   238.7663.2196
   248.7   661.9     261  662.22  267.18663.2145   271.8  663.88   283.5  662.61
   297.6  663.12   301.7  664.34   311.7  669.23   325.3  672.77   338.3  679.07
   353.9  683.51   395.3  690.75   411.6  696.88   430.5  702.12   450.9  703.71
#Mann= 3 ,-1,0
       0      .1       0   238.7    .045       0  267.18      .1       0
#XS Ineff= 2 , 0
          220.75  677.74
Permanent Ineff=
       F       F
Bank Sta=238.7,267.18
XS Rating Curve= 0 ,0
Exp/Cntr(USF)=0,0
Exp/Cntr=0.3,0.1

Type RM Length L Ch R = 1 ,4902    ,232.7,231.2,225.3
XS GIS Cut Line= 3
1596679.56706047470793.7504020951596846.39749562470753.825169752
1597134.42952895470869.323163315
#Sta/Elev= 30
       0  723.68    10.2  717.25    30.5  699.04    47.3  686.94    64.2  679.23
    87.8  674.45   111.4  665.11   124.9     662   128.3  662.35     135  665.08
   138.4  665.51   175.7  666.22   219.5   664.8     257  661.35   274.7  660.43
   284.4661.3314   289.2  661.76   299.4  665.18   334.8  665.96   352.5  665.17
     356  666.51   363.1  673.27   366.6  675.68   377.2  680.32   387.8  686.71
   391.3  687.86   423.7  695.24   440.8  696.83   453.3  699.06   481.9  706.25
#Mann= 3 ,-1,0
       0      .1       0     257    .045       0   284.4      .1       0
#XS Ineff= 2 , 0
          171.28   682.3
Permanent Ineff=
       F       F
Bank Sta=257,284.4
XS Rating Curve= 0 ,0
Exp/Cntr(USF)=0,0
Exp/Cntr=0.3,0.1

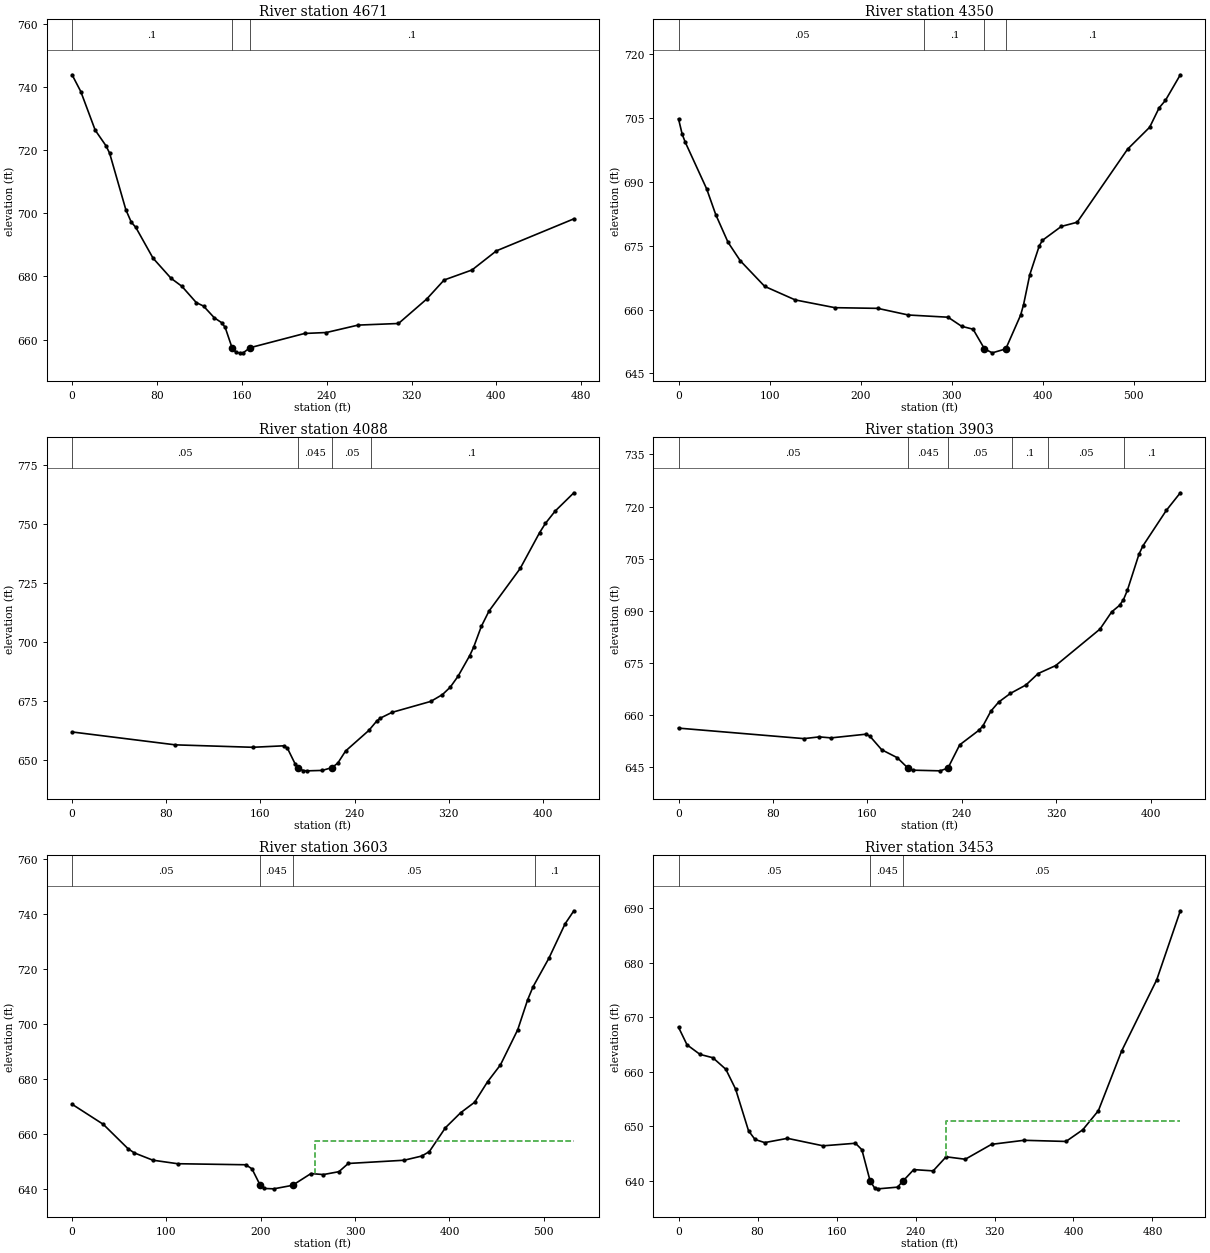
Type RM Length L Ch R = 1 ,4671    ,318.3,320.4,319.6
XS GIS Cut Line= 4
1596652.10706565 471011.583591411596882.23857559470947.908829947
1596955.53184453470968.1332462311597113.53309973470959.817390695
#Sta/Elev= 30
       0  743.91     8.2  738.61    21.8  726.36      32   721.4    35.4  719.06
    50.7  701.14    55.8  697.22    60.1  695.54    76.3  685.81    93.3  679.42
   103.5  676.89   117.1  671.72   123.9  670.62   134.1   666.9   140.9  665.38
   144.3  663.88  150.79657.4238   154.6  655.93     158   655.8   161.4  655.84
  167.76657.4233   219.2  661.94   239.7  662.24   269.6  664.59   307.7   665.1
   334.3  672.85   350.7  678.88     377  682.06     400  688.12     473  698.26
#Mann= 3 ,-1,0
       0      .1       0  150.79    .045       0  167.76      .1       0
Bank Sta=150.79,167.76
XS Rating Curve= 0 ,0
Exp/Cntr(USF)=0,0
Exp/Cntr=0.3,0.1

Type RM Length L Ch R = 1 ,4350    ,256.2,262.1,266.2
XS GIS Cut Line= 3
1596646.22691249471163.8855335151596943.05806123471228.003731746
1597177.45786386471148.795805609
#Sta/Elev= 30
       0  704.81       4  701.22     7.4  699.33    30.9  688.37    40.9  682.31
    54.4  675.81    67.8  671.49    94.6  665.47   128.2  662.28   171.8  660.46
   218.8   660.3   252.4  658.74     296  658.22   310.9  656.09   323.5   655.4
  336.03650.7766   344.6  649.85  359.38 650.778   375.7  658.71   378.9  661.14
   385.8  668.24   396.2     675   399.7  676.29   420.4  679.55   437.8  680.53
   493.2  697.71   517.4  702.85   527.8   707.4   534.7  709.15   551.1  715.18
#Mann= 4 ,-1,0
       0     .05       0     270      .1       0  336.03    .045       0
  359.38      .1       0
Bank Sta=336.03,359.38
XS Rating Curve= 0 ,0
Exp/Cntr(USF)=0,0
Exp/Cntr=0.3,0.1

Type RM Length L Ch R = 1 ,4088    ,184.9,185.8,187
XS GIS Cut Line= 6
1596801.92796968471470.1644794971596890.09216343471468.271438662
   1596965.56675471467.5647471581597065.39561859 471474.38166267
1597139.99651927471482.1093374971597227.03079401471491.125067491
#Sta/Elev= 30
       0  661.94    87.7  656.49   153.4  655.46   179.6  656.08   182.9  655.08
   189.5   648.4  191.88 646.878   196.1  645.64   199.8   645.5   212.5  645.68
  220.82646.8774   225.7  648.77   232.3  653.88     252  662.56   258.6  666.46
   261.9  667.81   271.7  670.22   304.7  674.87   314.6  677.75   321.2  680.88
   327.8  685.47   337.7  694.19     341  697.69   347.6  706.57   354.1  713.05
   380.6  731.07   397.1  746.23   402.1  750.18   410.3  755.34   426.2  763.09
#Mann= 4 ,-1,0
       0     .05       0  191.88    .045       0  220.82     .05       0
  253.66      .1       0
Bank Sta=191.88,220.82
XS Rating Curve= 0 ,0
Exp/Cntr(USF)=0,0
Exp/Cntr=0.3,0.1

Type RM Length L Ch R = 1 ,3903    ,300.4,300,298.2
XS GIS Cut Line= 6
1596803.46078876471637.3926529291596890.87465592471643.132798925
1596965.49589776471650.7197260111597064.84806126471662.083220333
1597139.36234793471670.6055130061597226.29557301471680.548406512
#Sta/Elev= 30
       0  656.26   106.2  653.24   119.3  653.74   129.2  653.45   158.9  654.52
   162.2   653.9   172.1  650.04   185.3  647.75  194.27644.7839   198.5  644.16
   221.7  643.97  228.27644.7843   238.2  651.45   254.7   655.7     258  656.97
   264.6  661.14   271.2  663.75   281.2  666.26   294.3  668.67   304.7  671.97
   319.5  674.25     357  684.74   366.9  689.68   373.6  691.58   376.9  693.21
   380.2  695.87   390.1  706.33   393.4  708.69   413.2  718.89   425.1  723.97
#Mann= 6 ,-1,0
       0     .05       0  194.27    .045       0  228.27     .05       0
  282.61      .1       0  312.61     .05       0  377.61      .1       0
Bank Sta=194.27,228.27
XS Rating Curve= 0 ,0
Exp/Cntr(USF)=0,0
Exp/Cntr=0.3,0.1

Type RM Length L Ch R = 1 ,3603    ,150.2,149.3,148.6
XS GIS Cut Line= 6
1596751.64593175471940.5905373391596839.03191184471945.059032336
1596913.93399301471948.8894052511597013.80354393471953.996350423
1597121.50135165471963.5303279571597275.81446312471917.003600047
#Sta/Elev= 30
       0   670.7    33.1  663.38    59.3  654.51    65.9  652.98    85.6  650.32
   111.9  649.03   184.2  648.65   190.7  647.14  199.42641.1672   203.9  640.02
   213.7  639.88  233.65641.1655   253.2  645.45   266.3  645.08   282.8  646.13
   292.7  649.12   351.9   650.3   370.6  651.83   378.6  653.43   395.7  662.15
   411.7  667.57   426.6  671.42   440.3  678.87     454  685.04   472.3  697.84
   482.8  708.74   488.6  713.53   505.4  723.93   522.5  736.42   531.8  741.18
#Mann= 4 ,-1,0
       0     .05       0  199.42    .045       0  233.65     .05       0
  490.62      .1       0
#XS Ineff= 2 , 0
                          257.43          657.13
Permanent Ineff=
       F       F
Bank Sta=199.42,233.65
XS Rating Curve= 0 ,0
Exp/Cntr(USF)=0,0
Exp/Cntr=0.3,0.1

Type RM Length L Ch R = 1 ,3453    ,32.9,32.9,32.9
XS GIS Cut Line= 2
 1596746.5693487472100.1667610831597254.76365476472101.179100338
#Sta/Elev= 30
       0  668.15     8.6  664.94    21.7  663.19    34.8  662.57    47.9  660.46
    57.8  656.83    70.9  649.19    77.5   647.6    87.3  647.03   110.3  647.81
   146.4  646.44   179.2  646.91   185.7  645.72  194.01  640.01   198.8  638.65
   202.1  638.56   221.8  638.87  227.41  640.01   238.2  642.08   257.9  641.85
     271  644.43   290.4  643.98     317  646.71   349.8  647.45   392.4  647.24
   409.4  649.38   425.2  652.87   448.8  663.82   484.3  676.85   508.2  689.49
#Mann= 3 ,-1,0
       0     .05       0  194.01    .045       0  227.41     .05       0
#XS Ineff= 2 , 0
                          270.43          651.06
Permanent Ineff=
       F       F
Bank Sta=194.01,227.41
XS Rating Curve= 0 ,0
Exp/Cntr(USF)=0,0
Exp/Cntr=0.3,0.1

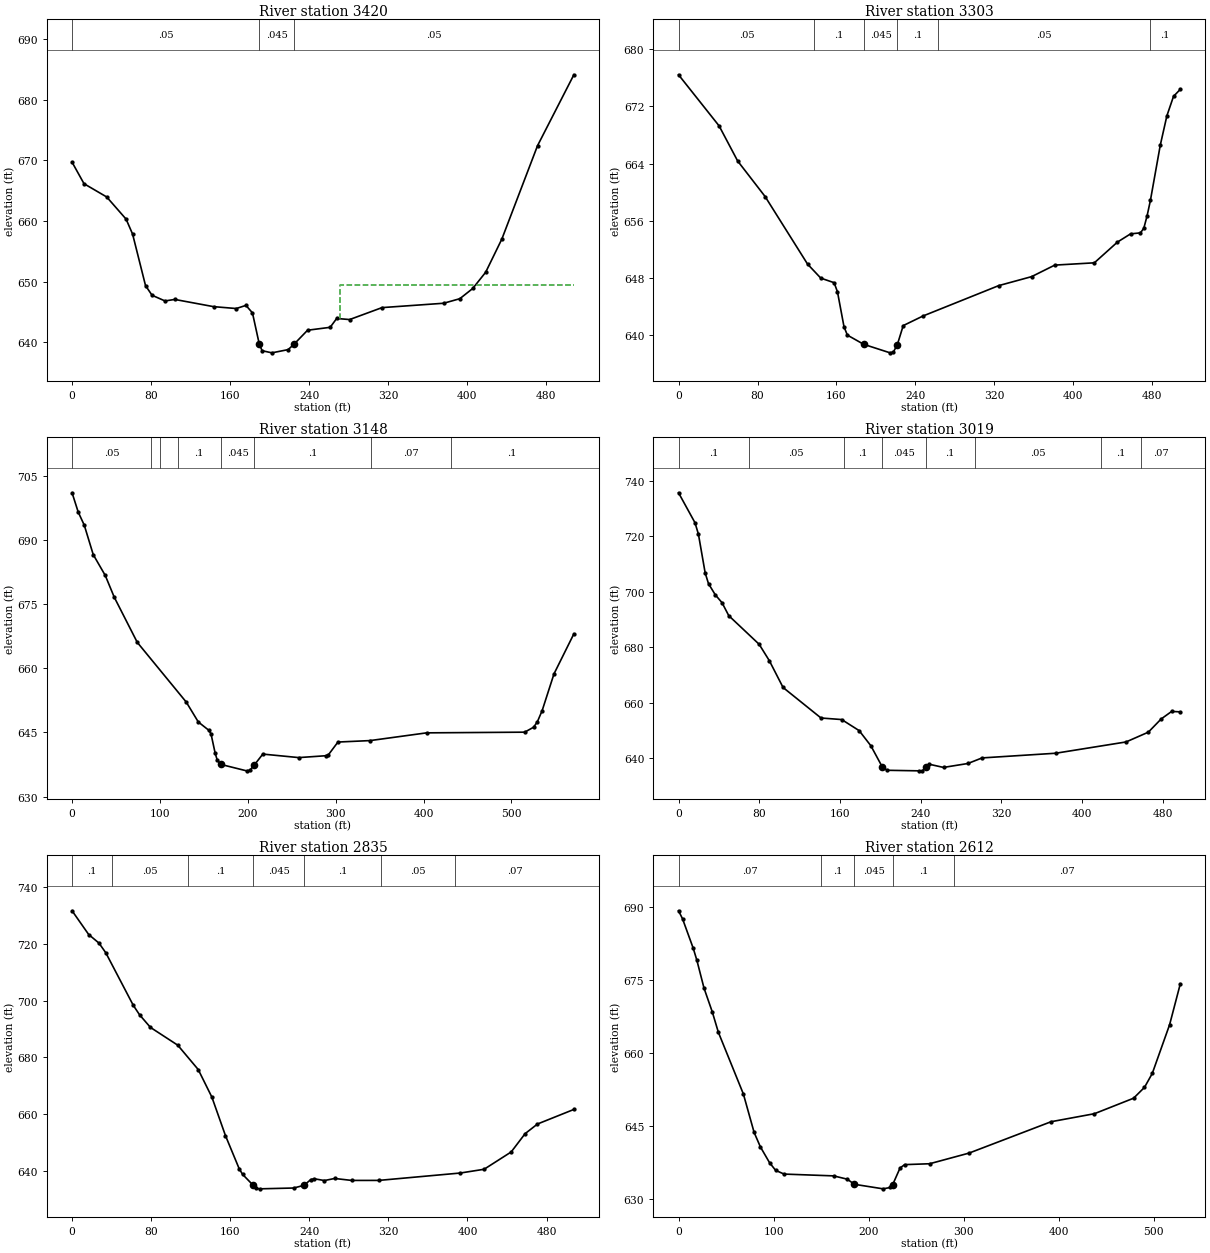
Type RM Length L Ch R = 1 ,3420    ,113.5,117.7,119.7
XS GIS Cut Line= 2
1596749.60636647472133.0677868741597257.80067252472134.080126129
#Sta/Elev= 30
       0   669.7    12.1  666.15    35.1  663.96    54.7  660.31    61.3  657.84
    74.4  649.34      81  647.75    94.1  646.81     104  647.06   143.3  645.87
   166.3  645.56   176.1  646.08   182.7  644.84  189.64  639.66   192.5   638.6
   202.4  638.25   218.8  638.78   224.7639.6579   238.5  641.98   261.4  642.46
     268  643.92   281.1  643.74   313.9  645.71   376.3  646.43   392.7  647.18
   405.8  648.87   418.9  651.55   435.3  657.03   471.4  672.42   508.2  684.12
#Mann= 3 ,-1,0
       0     .05       0  189.64    .045       0   224.7     .05       0
#XS Ineff= 2 , 0
                           271.1          649.47
Permanent Ineff=
       F       F
Bank Sta=189.64,224.7
XS Rating Curve= 0 ,0
Exp/Cntr(USF)=0,0
Exp/Cntr=0.3,0.1

Type RM Length L Ch R = 1 ,3303    ,146.6,154.2,156.8
XS GIS Cut Line= 6
1596742.76110701472204.3390255871596828.00765568472224.744168505
1596901.23093443  472241.36224551596999.63887408472259.136816248
1597073.48682351472272.2325905861597240.91885693472304.621917193
#Sta/Elev= 30
       0  676.41    41.1  669.26    59.9  664.35    87.7  659.38   130.7  649.93
   144.1  647.97   157.6  647.33     161  646.05   167.6  641.18     171     640
   187.6  638.71   214.3  637.52   217.6  637.62  221.66 638.672   227.6  641.33
   247.6  642.67   324.3  646.92   357.7  648.18   381.1  649.79   421.2  650.11
   444.6  653.01   457.9  654.16   467.9   654.3   471.3  654.94   474.6  656.66
     478  658.84     488  666.57   494.7  670.68   501.4  673.39   508.3  674.38
#Mann= 6 ,-1,0
       0     .05       0  137.65      .1       0   187.6    .045       0
  221.66      .1       0  262.74     .05       0  477.74      .1       0
Bank Sta=187.6,221.66
XS Rating Curve= 0 ,0
Exp/Cntr(USF)=0,0
Exp/Cntr=0.3,0.1

Type RM Length L Ch R = 1 ,3148    ,135.4,129.8,131.7
XS GIS Cut Line= 4
1596702.44437885472326.8724467581596844.10987769472367.926494823
1596909.31958616472401.2896014821597249.01667214472486.972125401
#Sta/Elev= 30
       0  701.09       7  696.57    13.9   693.5    24.1  686.61    37.8  681.73
      48  676.65    74.2  666.08     130  652.09   143.7  647.44   155.6  645.51
   158.1  644.69   162.9   640.1   165.2  638.55   169.2  637.52   198.6  636.01
   202.3  636.12  207.45637.3933   217.1  639.93     258  639.11   289.1  639.55
   291.8  639.78   302.6  642.75   339.2  643.09   403.5   644.9   515.1  645.06
   525.3  646.22   529.6  647.51     535   650.1   548.5  658.71   571.1  668.07
#Mann= 8 ,-1,0
       0     .05       0      90      .1       0     100     .05       0
     120      .1       0   169.2    .045       0  207.45      .1       0
  340.74     .07       0  430.74      .1       0
Bank Sta=169.2,207.45
XS Rating Curve= 0 ,0
Exp/Cntr(USF)=0,0
Exp/Cntr=0.3,0.1

Type RM Length L Ch R = 1 ,3019    ,185.8,184,183.8
XS GIS Cut Line= 6
1596653.79898052  472455.84202711596740.52026376472473.004394354
1596812.69170735472493.8547463441596907.01861843472527.057763936
1596977.76388377472551.9602731781597127.31716222472605.253356232
#Sta/Elev= 30
       0  735.69    16.3  724.89    19.7  720.77    26.4  706.77    29.7   702.9
    36.4  698.89    43.1  696.04    49.8  691.35    79.9  681.03      90  675.11
   103.6  665.45   141.2  654.44   161.7  653.88     179  649.89   190.6  644.43
  201.89636.8152   206.8  635.58   238.2  635.38   241.6  635.38   245.1  636.65
   248.6  637.75   262.6  636.61   286.8  638.03   300.8  640.04   373.8  641.73
   443.5   645.8   465.6  649.33   478.3  654.09   488.7  656.81   497.3  656.66
#Mann= 8 ,-1,0
       0      .1       0      70     .05       0  163.53      .1       0
  201.89    .045       0   245.1      .1       0  293.53     .05       0
  418.53      .1       0  458.53     .07       0
Bank Sta=201.89,245.1
XS Rating Curve= 0 ,0
Exp/Cntr(USF)=0,0
Exp/Cntr=0.3,0.1

Type RM Length L Ch R = 1 ,2835    ,216,222.4,225
XS GIS Cut Line= 6
1596598.23575862472616.4852904841596680.88880854472645.259839238
1596752.21346905472668.4504096521596847.31301637472699.371279568
1596918.63734879472722.5618499821597081.69991739472771.006087474
#Sta/Elev= 30
       0  731.62    16.8  723.27    27.2  720.25    34.1  716.85    61.9  698.35
    68.3  694.99    79.3  690.56   106.9  684.31   127.6  675.74   141.4  666.05
   155.2  652.45     169  640.86   172.5  638.83  183.16 635.006   186.3  633.86
   189.7  633.74   224.2  634.03   234.6  634.98   241.5     637   244.9  637.29
   255.3  636.66   265.6  637.39   282.9   636.7   310.3  636.71   392.8  639.31
   416.8  640.63   444.2  646.72   458.3  653.17   470.8  656.56   507.6  661.69
#Mann= 7 ,-1,0
       0      .1       0      40     .05       0  117.52      .1       0
  183.16    .045       0   234.6      .1       0  312.52     .05       0
  387.52     .07       0
Bank Sta=183.16,234.6
XS Rating Curve= 0 ,0
Exp/Cntr(USF)=0,0
Exp/Cntr=0.3,0.1

Type RM Length L Ch R = 1 ,2612    ,208.1,212.3,213.4
XS GIS Cut Line= 2
1596531.65812946472784.0145879741596991.36848495  473043.4042299
#Sta/Elev= 30
       0  689.14     4.2   687.5    15.5  681.42    19.3  678.97    26.8  673.26
    35.5  668.38    41.9  664.19    68.2  651.53    79.5  643.64    86.1  640.67
    95.7  637.44   102.1  635.86     111  635.09   163.2  634.72   177.5  634.04
     185  632.99   215.2  632.06   222.7  632.34   225.3632.9429     233  636.34
   237.8  637.03   264.1  637.21   305.6   639.4   391.9  645.84   437.4  647.48
   478.6  650.66   490.1  652.89   498.3  655.75   516.5  665.74   527.8  674.16
#Mann= 5 ,-1,0
       0     .07       0     150      .1       0     185    .045       0
   225.3      .1       0     290     .07       0
Bank Sta=185,225.3
XS Rating Curve= 0 ,0
Exp/Cntr(USF)=0,0
Exp/Cntr=0.3,0.1

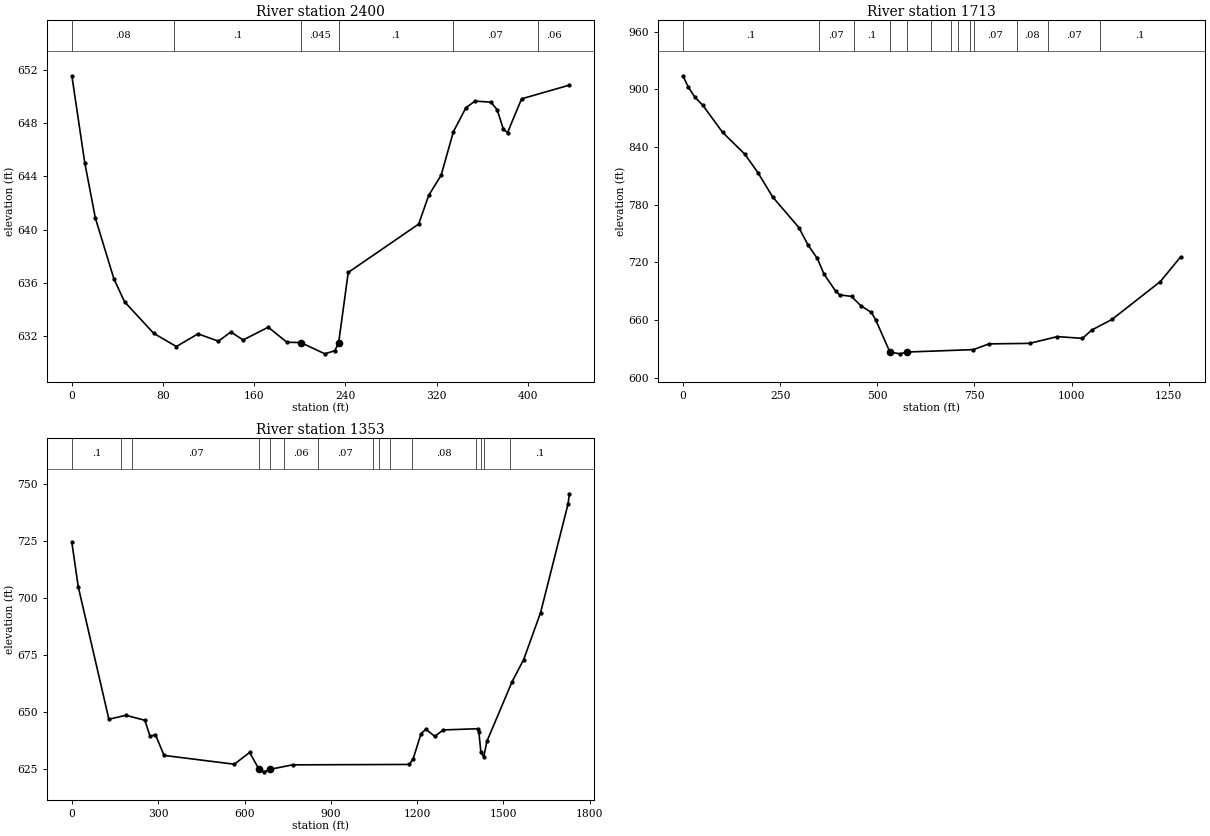
Type RM Length L Ch R = 1 ,2400    ,669.6,687.1,690.6
XS GIS Cut Line= 6
1596440.76466376472917.1394372581596503.91906501472989.421773002
1596566.03377017473036.7100642621596645.71536934473097.132515594
1596705.47640467473142.4493540821596775.73709093473194.607386261
#Sta/Elev= 30
       0  651.54    11.3  645.02    20.6  640.87    36.9   636.3    46.2  634.58
    71.8  632.21    91.7  631.22   110.7  632.17   128.6  631.62   139.5  632.31
   150.3  631.71   172.3  632.67   188.7  631.54   200.9 631.515     222  630.67
   230.8  630.91  234.11631.5165   242.5  636.78   304.3  640.41   313.1  642.56
     324  644.07   334.8  647.35   345.7  649.13   353.7  649.64   367.7  649.56
   373.2  648.99   378.7  647.51   382.3  647.28   394.6  649.81   436.6  650.84
#Mann= 6 ,-1,0
       0     .08       0      90      .1       0   200.9    .045       0
  234.11      .1       0  334.05     .07       0  409.05     .06       0
Bank Sta=200.9,234.11
XS Rating Curve= 0 ,0
Exp/Cntr(USF)=0,0
Exp/Cntr=0.3,0.1

Type RM Length L Ch R = 1 ,1713    ,375.1,359.6,357.4
XS GIS Cut Line= 4
 1595853.3663333472739.8269985621595997.38234997473300.206152512
1596228.37833709473606.7749008561596536.37298659473686.625365541
#Sta/Elev= 30
       0  914.04    13.9  902.18    30.8  891.74    51.2  883.34     102  855.19
   159.6  832.35   193.4  813.02   230.7  788.12   298.4   756.1   322.1  737.85
   345.9  723.99   362.8  707.93   393.2  689.88   403.4  686.17   433.9  684.53
   457.6  674.92     485  667.82   495.8  660.33  532.69626.6558   559.3   624.8
  575.41626.6549   747.4  629.19   787.7  635.15     892  635.68   963.5  642.74
  1028.1  640.91  1052.5  649.63  1104.3  660.63  1228.7  700.01  1280.6  725.56
#Mann= 13 ,-1,0
       0      .1       0     350     .07       0     440      .1       0
  532.69    .045       0  575.41      .1       0  638.59     .08       0
  688.59      .1       0  708.59     .08       0  738.59      .1       0
  748.59     .07       0  858.59     .08       0  938.59     .07       0
 1072.44      .1       0
Bank Sta=532.69,575.41
XS Rating Curve= 0 ,0
Exp/Cntr(USF)=0,0
Exp/Cntr=0.3,0.1

Type RM Length L Ch R = 1 ,1353    ,,,
XS GIS Cut Line= 6
1595475.67043593472799.1280161091595331.30451852473085.272340982
1595602.96683278473246.0964310241595865.93595299473476.466073517
1595965.90768463473598.1707903051596530.46222077473754.223027533
#Sta/Elev= 30
       0  724.54    22.1  705.09   128.7  646.78   187.5  648.53   253.7  646.34
     272  639.23   290.4  640.04   320.5  630.89   564.5  627.02   617.8  632.19
  650.68 624.757   668.9  623.67   688.3624.7572   766.9  626.74  1172.6  626.92
  1186.2  629.44  1213.4  640.47  1230.4  642.39  1261.4  639.24  1290.2  642.09
  1410.8  642.62  1414.2   641.4  1421.4  632.46  1431.3  630.22  1442.2  637.04
  1530.2  663.38  1570.2  673.05  1628.9  693.66    1724  741.26  1729.2   745.9
#Mann= 15 ,-1,0
       0      .1       0     170     .08       0     210     .07       0
  650.68    .045       0   688.3     .07       0   736.2     .06       0
  855.35     .07       0 1045.94     .06       0 1065.94     .07       0
 1105.94     .06       0 1183.45     .08       0 1403.45     .07       0
 1423.45     .08       0 1433.45     .07       0 1523.45      .1       0
Bank Sta=650.68,688.3
XS Rating Curve= 0 ,0
Exp/Cntr(USF)=0,0
Exp/Cntr=0.3,0.1
LCMann Table=0

Chan Stop Cuts=-1
Use User Specified Reach Order=0
Composite Channel Slope=5